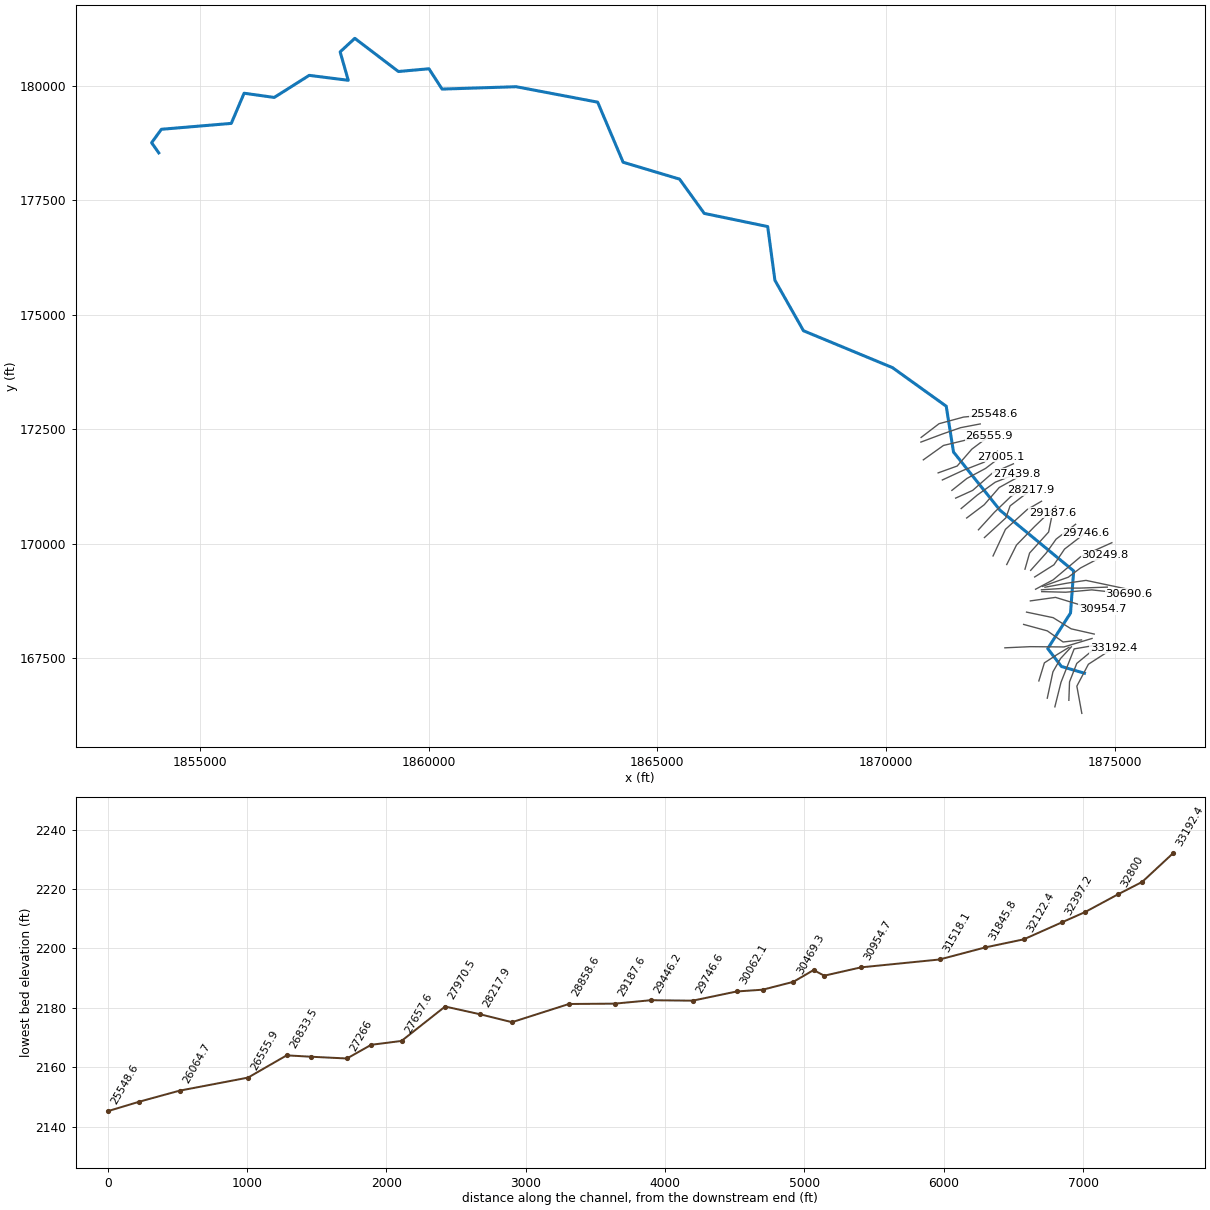
--- BeartownFk.prj (project) ---

Proj Title=BeartownFk
Current Plan=p01
Default Exp/Contr=0,0
English Units
Geom File=g01
Flow File=f01
Plan File=p01
BEGIN DESCRIPTION:
END DESCRIPTION:
DSS Export Rating Curves= 0
DSS Export Rating Curve Sorted= 0
DSS Export Volume Flow Curves= 0
DXF OffsetX= 0
DXF OffsetY= 0
DXF ScaleX= 0
DXF ScaleY= 0

--- BeartownFk.p01 (plan) ---

Plan Title=Floodplain
Program Version=4.00
Geom File=g01
Flow File=f01
K Sum by GR=0
Std Step Tol=0.01
Critical Tol=0.01
Num of Std Step Trials=20
Max Error Tol=0.3
Flow Tol Ratio=0.001
Split Flow NTrial=30
Split Flow Tol=0.02
Split Flow Ratio=0.02
Log Output Level=0
Friction Slope Method=1
Unsteady Friction Slope Method=2
Unsteady Bridges Friction Slope Method=1
Global Log Level=0
CheckData=False
Run HTab=0
Run UNet=0
Run PostProcess=0
UNET Theta=0
UNET Theta Warmup=0
UNET ZTol=0
UNET ZSATol=0
UNET MxIter=0
UNET MaxInSteps=0
UNET DtIC=0
UNET DtMin=0
UNET MaxCRTS=0
UNET WFStab=0
UNET SFStab=0
UNET WFX=0
UNET SFX=0
UNET DSS MLevel=0
UNET DZMax Abort=0
UNET Convert EG Bridges=0
UNET Use Existing IB Tables=0
UNET Froude Limit=0
UNET Froude Power=0
Write IC File=0
Echo Input=False
Echo Output=False
Write Detailed=0

--- BeartownFk.f01 (steady flow) ---

Flow Title=NFF Regression Equation
Program Version=4.00
Number of Profiles=1
Profile Names=P100yr
River Rch & RM=BeartownFk,Main      ,33192.4
574.6863
River Rch & RM=BeartownFk,Main      ,31845.8
584.1739
River Rch & RM=BeartownFk,Main      ,31845.8
823.8154
River Rch & RM=BeartownFk,Main      ,30954.7
838.3293
River Rch & RM=BeartownFk,Main      ,29746.6
917.3453
River Rch & RM=BeartownFk,Main      ,28858.6
933.7084
River Rch & RM=BeartownFk,Main      ,26064.7
1020.388
River Rch & RM=BeartownFk,Main      ,25126.3
1110.727
River Rch & RM=BeartownFk,Main      ,22091.7
1211.936
River Rch & RM=BeartownFk,Main      ,21171.8
1328.812
River Rch & RM=BeartownFk,Main      ,19092.8
1392.546
River Rch & RM=BeartownFk,Main      ,16015.6
1492.244
River Rch & RM=BeartownFk,Main      ,13188.7
1628.058
River Rch & RM=BeartownFk,Main      ,11360.3
1765.004
River Rch & RM=BeartownFk,Main      ,7105.6
1917.315
River Rch & RM=BeartownFk,Main      ,388.6
2033.554
Boundary for River Rch & Prof#=BeartownFk,Main      ,1
Up Type=0
Dn Type=3
Dn Slope=0.024256

--- BeartownFk.g01 (geometry) ---

Geom Title=USGS 10m DEM
Program Version=4.00

River Reach=BeartownFk      ,Main
Reach XY= 30
     1874330.789      167169.872     1873828.662      167316.791
     1873529.245      167707.335     1874027.193      168482.958
     1874096.463      169403.411     1872485.935      170729.399
      1871470.42      171999.689     1871311.365      173000.276
     1870136.342      173843.123     1868192.357      174647.951
     1867567.778      175750.285     1867410.093       176923.12
     1866024.146      177210.476     1865483.668      177959.469
     1864251.254       178327.74     1863694.178      179640.033
     1861913.073      179977.183     1860294.665      179925.314
     1860008.347      180369.315     1859340.271      180309.147
     1858387.842      181033.624     1858067.399      180737.587
     1858244.792       180117.23     1857391.023      180225.119
     1856627.508      179742.734     1855968.768      179835.062
     1855688.674      179176.322     1854161.495      179047.428
     1853947.778      178753.895     1854103.855      178532.369

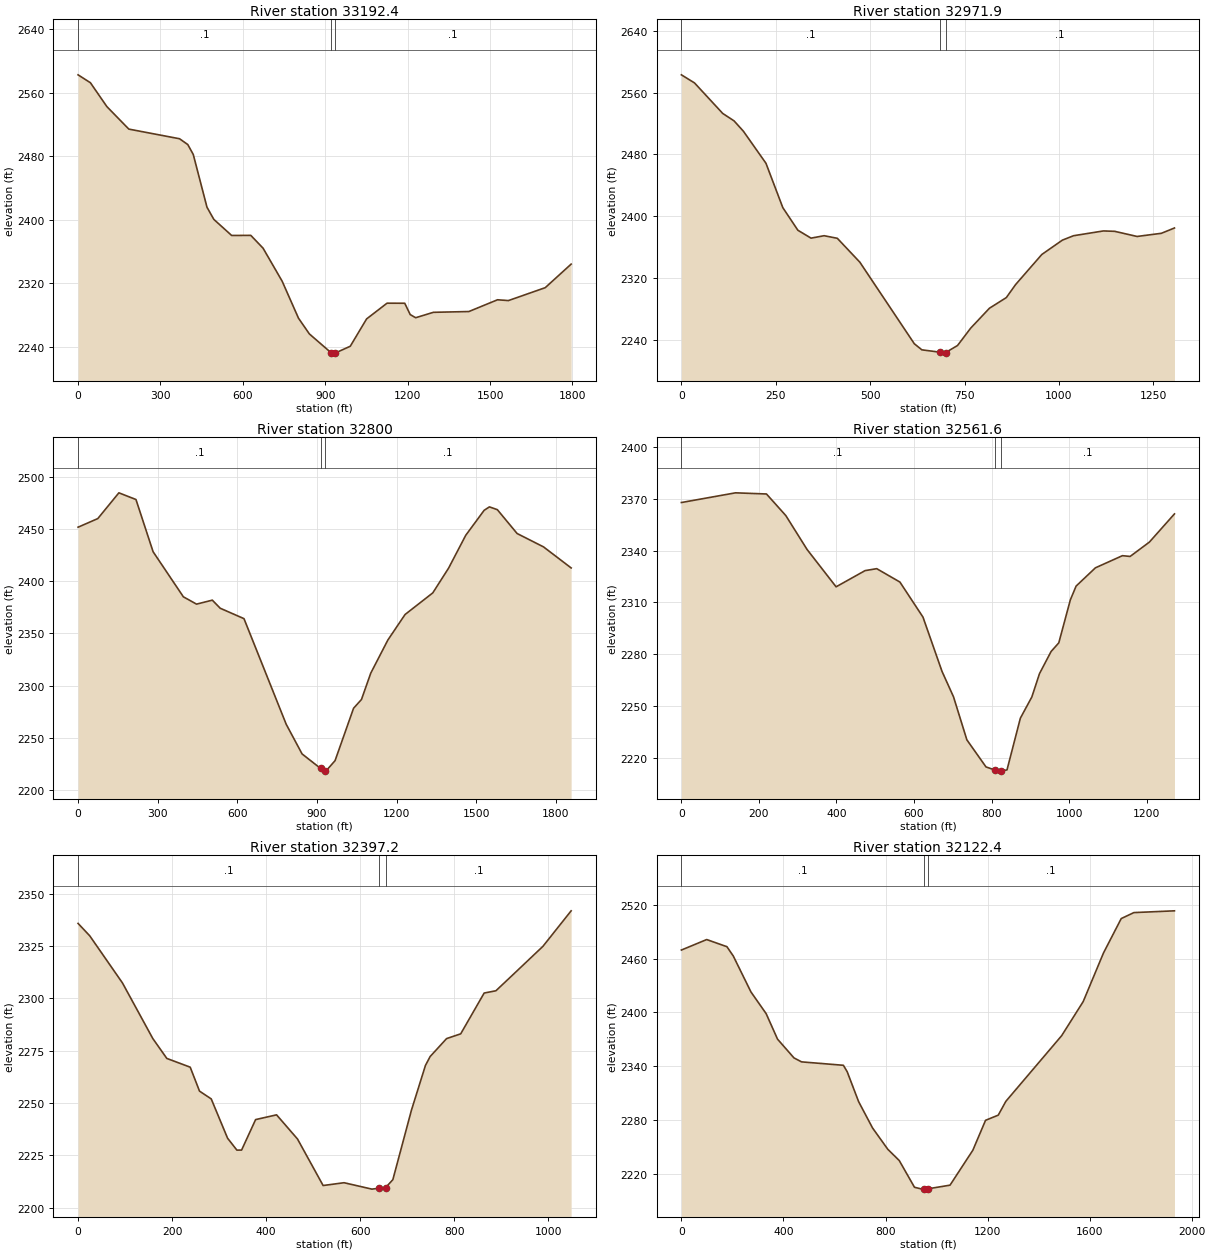
Type RM Length L Ch R = 1 ,33192.4 ,218,220.5,223.1
XS GIS Cut Line= 4
     1874274.281      166292.693     1874165.638      166887.033
     1874417.626      167365.378     1874964.482       167717.83
#Sta/Elev= 30
       0 2582.59    44.9 2572.64   104.9 2542.55   184.8 2514.21   369.5 2502.06
   399.5 2494.75   419.4 2482.31   469.4 2415.81   494.3 2400.49   559.2 2380.22
     629 2380.32   673.6 2364.19   743.1 2322.61   802.6 2276.01   842.3 2256.14
   921.4 2232.46   926.6 2231.98   936.4 2232.09   991.1 2240.64  1050.6 2275.07
    1125 2294.89  1189.5 2294.82  1209.4 2280.55  1229.3 2276.58  1293.8 2283.39
    1423 2284.37  1527.3 2299.19    1567 2298.18  1701.1 2314.45  1795.4 2344.12
#Mann= 3 , 0 , 0
       0      .1       0   921.4    .045       0   936.4      .1       0
Bank Sta=921.4,936.4
XS Rating Curve= 0 ,0
Exp/Cntr=0.3,0.1

Type RM Length L Ch R = 1 ,32971.9 ,172.1,172,171.8
XS GIS Cut Line= 4
     1873991.368      166578.297     1874005.756      166981.156
     1874164.022      167384.016     1874526.596      167683.283
#Sta/Elev= 30
       0 2583.05    34.8 2572.54   109.5    2533   139.4 2523.42   164.2    2510
     224 2468.45   268.7  2410.9   308.6 2381.61   343.4  2371.4   378.2 2374.54
   413.1 2371.18   472.8 2340.19     617 2234.54     637 2226.65   684.6 2223.61
   696.6 2222.38   699.6 2223.02   731.5 2232.28   766.3 2254.75     816 2280.56
   860.7 2294.35   885.4 2311.29   954.7  2350.2  1009.2 2368.82  1038.8 2374.54
    1118 2380.74  1147.7 2380.23  1207.1 2373.57  1271.4 2377.67  1306.1 2384.55
#Mann= 3 , 0 , 0
       0      .1       0   684.6    .045       0   699.6      .1       0
Bank Sta=684.6,699.6
XS Rating Curve= 0 ,0
Exp/Cntr=0.3,0.1

Type RM Length L Ch R = 1 ,32800   ,241.7,238.3,234.9
XS GIS Cut Line= 4
      1873685.43      166435.497     1873818.714      166969.646
      1874107.22      167700.865     1874621.204      167788.649
#Sta/Elev= 30
       0 2451.51    74.4 2459.76   153.8 2484.39   218.2 2477.98   282.7 2428.07
   396.8 2384.94   446.4 2377.95   505.9 2381.75   535.6 2374.02   625.2 2364.06
   784.4    2263   844.1 2234.69   913.7 2220.86   928.7 2218.51   933.6 2218.24
   968.4 2228.26  1038.1 2278.36  1067.9 2286.74  1102.8 2311.88  1167.4 2343.63
  1232.1    2368  1336.6  2388.7  1396.2 2412.36  1460.8 2443.76  1530.3 2467.71
  1550.1 2470.94  1579.9 2468.29  1654.4 2445.47  1753.8 2432.71    1858 2412.56
#Mann= 3 , 0 , 0
       0      .1       0   913.7    .045       0   928.7      .1       0
Bank Sta=913.7,928.7
XS Rating Curve= 0 ,0
Exp/Cntr=0.3,0.1

Type RM Length L Ch R = 1 ,32561.6 ,175.1,164.5,153.8
XS GIS Cut Line= 4
     1873519.446      166624.338     1873643.182      167199.852
     1873810.081      167490.486     1874046.042       167746.59
#Sta/Elev= 30
       0  2367.8   139.7 2373.42   219.5 2372.75   269.4 2360.25   324.3 2340.58
   399.1 2318.98   473.9 2328.36   503.9 2329.49   563.7 2321.74   623.2 2301.45
   672.4 2269.97     702 2255.27   736.5 2230.32   785.8 2214.66   808.9 2212.84
   823.9 2212.25   825.2 2212.22     840 2212.94   874.5  2242.9   904.1 2255.19
   923.8 2268.69   953.7  2281.5   973.6 2286.52  1003.4 2311.42  1018.3 2319.41
  1068.1 2329.98  1137.7 2337.01  1157.6 2336.57  1207.4  2344.9    1272 2361.21
#Mann= 3 , 0 , 0
       0      .1       0   808.9    .045       0   823.9      .1       0
Bank Sta=808.9,823.9
XS Rating Curve= 0 ,0
Exp/Cntr=0.3,0.1

Type RM Length L Ch R = 1 ,32397.2 ,287.4,274.8,261.8
XS GIS Cut Line= 4
     1873335.282      167001.299      1873456.14      167395.526
     1873729.509      167573.936     1873994.245       167735.08
#Sta/Elev= 30
       0 2335.75    24.8 2329.83    94.4 2307.31     159 2280.73   188.8 2271.24
   238.5 2267.06   258.3 2255.62   283.2 2251.91     318 2233.12   337.8 2227.43
   347.8 2227.46   377.6 2242.02   422.2 2244.29   466.7 2232.75   521.2 2210.52
   565.7 2211.86     625  2208.8   639.2  2209.2   654.2 2209.55   669.5 2213.31
   709.1 2246.57   738.8 2267.88   748.8 2272.14   783.8 2280.72   813.8 2282.99
   863.7 2302.48   888.7 2303.57   928.7 2312.04   988.7  2324.8  1048.7 2341.76
#Mann= 3 , 0 , 0
       0      .1       0   639.2    .045       0   654.2      .1       0
#XS Ineff= 2 , 0
          565.66 2211.83
Permanent Ineff=
       F       F
Bank Sta=639.2,654.2
XS Rating Curve= 0 ,0
Exp/Cntr=0.3,0.1

Type RM Length L Ch R = 1 ,32122.4 ,292.9,276.5,260.2
XS GIS Cut Line= 4
     1872593.513      167724.221      1873148.24      167749.468
     1873884.445      167743.393     1874497.957      167928.725
#Sta/Elev= 30
       0 2469.49    99.2 2481.18   178.5 2473.21   203.3 2462.88   272.7 2422.76
   332.2 2398.61   376.8  2370.2   441.3 2349.28     471 2344.87   634.9 2341.06
   649.8 2333.89   694.6 2300.54   749.3 2271.16     809 2247.45   853.8 2234.93
   913.5 2205.13   943.3 2203.06   951.1 2203.19   966.1  2203.4  1052.8 2207.48
  1142.3 2246.44    1192 2279.74  1241.8 2285.51  1271.6 2300.89  1490.3 2374.06
  1574.7 2412.04  1654.2  2466.2  1723.8 2504.58  1773.4 2511.22  1932.4 2513.19
#Mann= 3 , 0 , 0
       0      .1       0   951.1    .045       0   966.1      .1       0
Bank Sta=951.1,966.1
XS Rating Curve= 0 ,0
Exp/Cntr=0.3,0.1

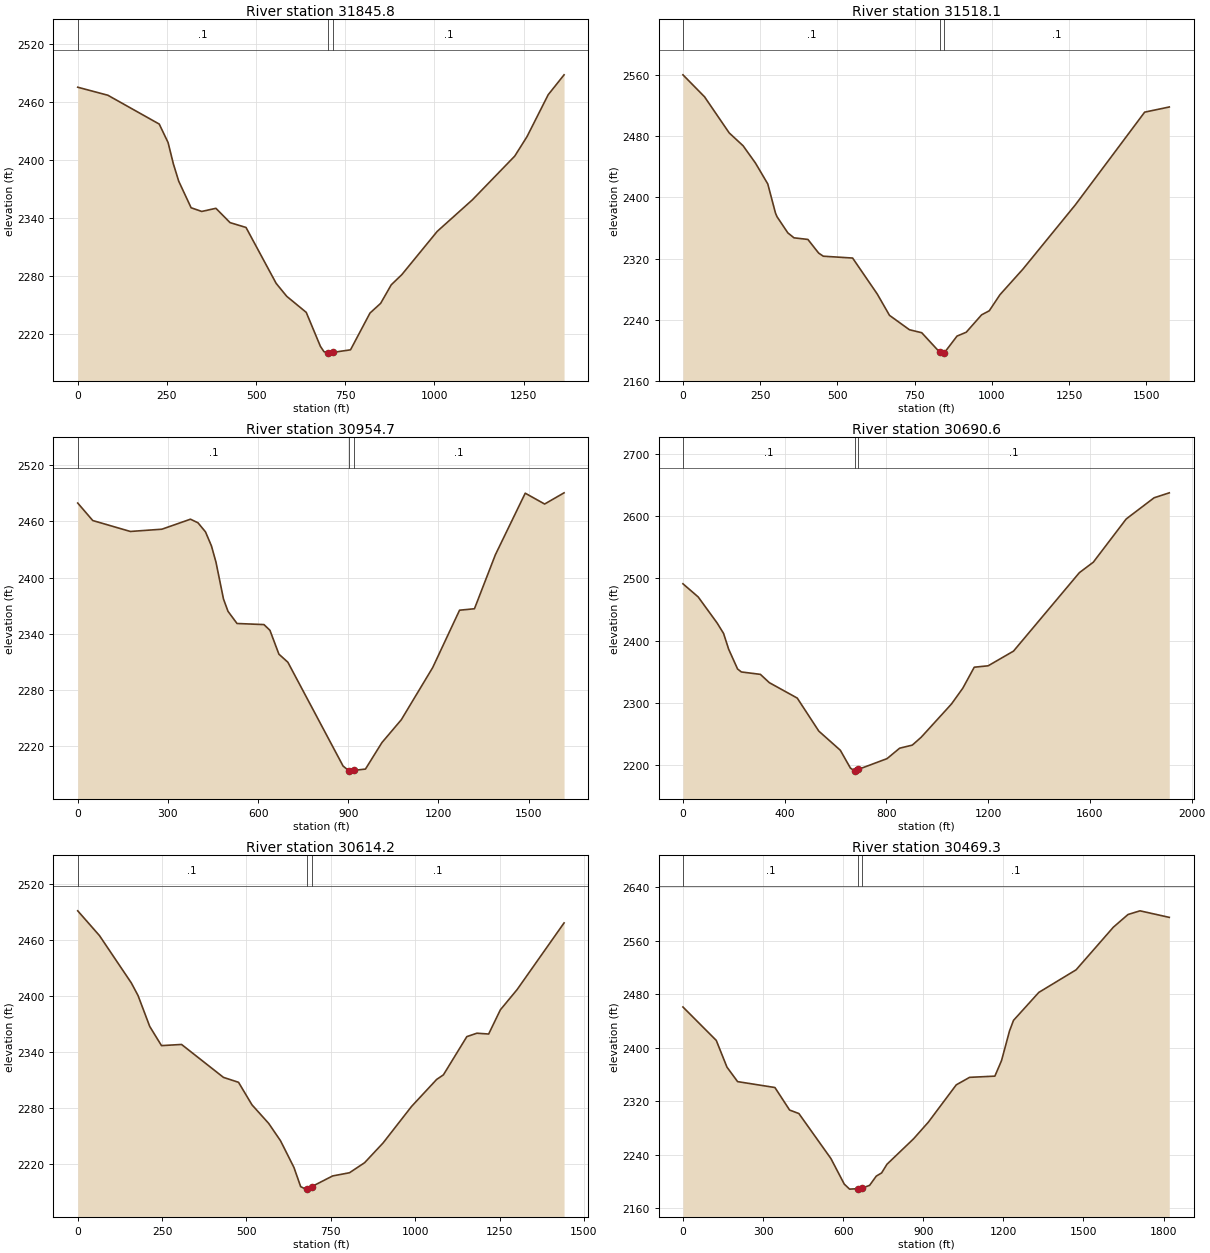
Type RM Length L Ch R = 1 ,31845.8 ,326.4,327.8,329.1
XS GIS Cut Line= 4
     1873002.521      168235.146     1873520.172      168094.549
     1873865.273      167851.701      1874267.89      167896.436
#Sta/Elev= 30
       0  2475.5    84.4 2467.21   228.5 2437.37   253.3 2418.25   268.2  2396.1
   283.1 2378.29   317.9 2350.76   347.7 2346.95   387.4  2350.2   427.1 2335.38
   471.8 2330.39   556.3 2272.52     586 2259.11   640.7  2242.5   680.4 2207.33
   690.3 2201.86   701.4 2200.44   705.2 2200.34   716.4 2201.16   764.8 2203.76
   819.4 2241.82   849.2 2251.83     879 2271.05   908.7  2281.6  1007.8  2326.3
  1106.6 2359.02  1225.2 2404.22  1259.7 2424.44    1319 2467.73  1363.5 2488.33
#Mann= 3 , 0 , 0
       0      .1       0   701.4    .045       0   716.4      .1       0
Bank Sta=701.4,716.4
XS Rating Curve= 0 ,0
Exp/Cntr=0.3,0.1

Type RM Length L Ch R = 1 ,31518.1 ,553.2,563.4,566.6
XS GIS Cut Line= 4
     1873066.429      168503.893     1873647.987      168382.468
     1874040.591      168139.059     1874545.944      168024.585
#Sta/Elev= 30
       0  2560.4    69.9 2531.64   149.8 2484.36   194.7 2467.58   234.6 2445.04
   274.6 2417.61   299.6 2379.39   304.5 2374.75   339.5 2353.62   359.5 2347.14
   404.4 2345.04   439.3 2327.14   454.3 2323.08   549.2 2320.68   628.9 2273.64
   668.6  2245.7   733.2 2226.86   772.9 2222.98   830.9 2197.55   842.4 2196.28
   845.9 2196.68   887.2 2218.59     917 2223.64   966.6 2246.35   991.5 2251.68
  1026.2 2272.75  1100.9  2306.4  1270.3 2390.38  1494.5 2511.57  1574.2 2518.34
#Mann= 3 , 0 , 0
       0      .1       0   830.9    .045       0   845.9      .1       0
Bank Sta=830.9,845.9
XS Rating Curve= 0 ,0
Exp/Cntr=0.3,0.1

Type RM Length L Ch R = 1 ,30954.7 ,256.2,264.1,283.3
XS GIS Cut Line= 4
     1873149.509       168748.97     1873699.113      168825.659
     1874364.353      168623.246     1874728.444      168572.413
#Sta/Elev= 30
       0 2479.56      50 2460.91     175 2449.25     280 2451.66     375 2462.32
     400 2458.51     425 2448.82   444.9 2433.78   459.9 2416.52   484.9  2377.2
   499.9 2364.09   529.9 2351.09   619.5 2349.93   639.4 2343.85   669.2  2318.4
     699  2309.8   882.7 2199.08   903.4 2193.68   907.6 2193.63   918.4  2194.4
   957.2 2195.83  1011.9 2224.04  1076.4 2248.42  1180.8 2304.06  1270.2 2365.26
  1319.8 2366.82  1389.4 2424.42  1488.7 2490.06  1553.3 2478.52  1617.9 2490.46
#Mann= 3 , 0 , 0
       0      .1       0   903.4    .045       0   918.4      .1       0
Bank Sta=903.4,918.4
XS Rating Curve= 0 ,0
Exp/Cntr=0.3,0.1

Type RM Length L Ch R = 1 ,30690.6 ,78.4,76.4,74.3
XS GIS Cut Line= 4
     1873398.748      168951.245     1873922.789      168938.464
     1874491.566       168989.59     1875303.191      168900.119
#Sta/Elev= 30
       0 2491.41    59.9 2470.29   134.8 2428.24   159.8 2411.63   179.7 2386.41
   214.7 2354.73   229.6 2349.95   304.5 2346.06   339.5 2332.79   449.3 2308.02
   534.1 2255.02   618.6 2224.35   658.3 2195.74   674.8 2191.13   678.1 2190.83
   689.8 2193.69   802.3  2210.9   851.9 2227.63   901.6 2232.57   936.4 2245.14
  1055.5  2298.5  1100.2 2323.97  1145.1 2357.56  1199.8 2359.83  1299.4 2383.36
  1558.3 2509.22  1613.1 2526.04  1742.5 2595.43  1852.1 2629.39  1911.8 2637.34
#Mann= 3 , 0 , 0
       0      .1       0   674.8    .045       0   689.8      .1       0
Bank Sta=674.8,689.8
XS Rating Curve= 0 ,0
Exp/Cntr=0.3,0.1

Type RM Length L Ch R = 1 ,30614.2 ,141.7,144.9,148.1
XS GIS Cut Line= 4
     1873391.681      168991.276     1873961.281      169028.424
     1874230.603      169028.424      1874831.16      169050.094
#Sta/Elev= 30
       0 2490.94    64.5 2464.36   158.8 2413.68   178.7 2400.17   213.4 2367.02
   248.2  2346.5   307.7 2347.74   431.8 2312.47   476.5 2307.18   516.2 2283.12
   565.8 2263.16   600.7 2244.68   640.6 2216.02   660.6  2195.4   675.6 2192.72
   678.1 2192.86   693.1 2195.34   755.4 2206.86   805.2 2210.26   850.1 2221.05
   904.7 2242.16   989.1 2281.29  1063.6 2310.28  1083.5 2315.15    1153 2356.14
  1182.8  2359.8  1217.6 2358.92  1252.4 2384.89    1302 2406.58  1441.1 2477.99
#Mann= 3 , 0 , 0
       0      .1       0   678.1    .045       0   693.1      .1       0
Bank Sta=678.1,693.1
XS Rating Curve= 0 ,0
Exp/Cntr=0.3,0.1

Type RM Length L Ch R = 1 ,30469.3 ,190.4,219.5,267.9
XS GIS Cut Line= 4
     1873469.046      169047.106      1873955.09      169136.772
     1874365.452      169196.885     1875258.456      169008.762
#Sta/Elev= 30
       0 2461.08   124.8 2411.13   164.8  2371.2   204.7  2349.5   344.5 2340.68
   399.4 2307.05   434.3 2301.74   554.2 2234.48   604.2 2196.27   624.2 2188.76
   656.1 2189.43   671.1 2190.26   699.1 2194.39   724.1 2208.21   744.1 2212.98
   764.1  2225.9     864 2264.08     919 2288.81  1023.7 2344.68  1073.6 2355.89
  1168.3  2357.7  1193.2 2380.87  1223.2 2425.29  1238.1 2441.08  1332.9 2482.89
  1472.5 2516.64  1612.1 2580.39    1667 2599.38  1711.9 2604.87  1821.6 2595.08
#Mann= 3 , 0 , 0
       0      .1       0   656.1    .045       0   671.1      .1       0
Bank Sta=656.1,671.1
XS Rating Curve= 0 ,0
Exp/Cntr=0.3,0.1

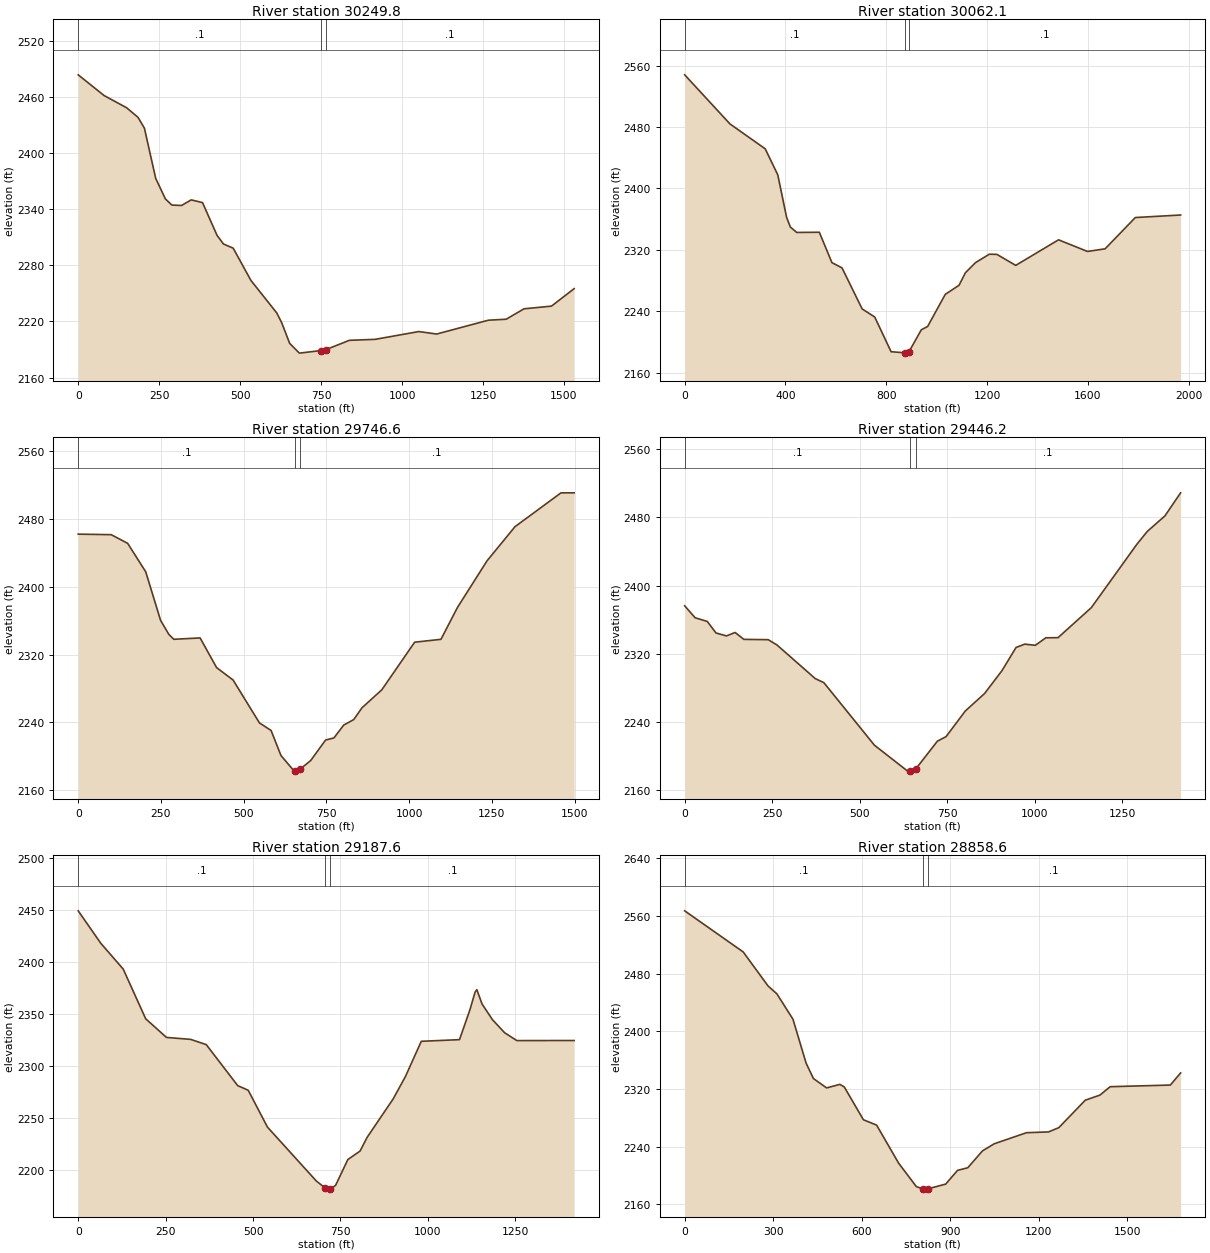
Type RM Length L Ch R = 1 ,30249.8 ,204.9,187.7,187.7
XS GIS Cut Line= 4
     1873416.446      169065.572     1873979.855      169266.789
     1874246.082      169468.007     1874776.944      169746.501
#Sta/Elev= 30
       0  2483.8    79.8 2461.67   149.6 2448.55   184.5 2438.39   204.4 2426.81
   239.3 2373.05   269.2 2351.08   289.2  2344.5   319.1 2344.07     349 2350.04
   383.9 2347.12   428.8 2312.06   448.7  2302.8   478.6 2298.38   533.4 2263.86
   613.2 2229.08   628.2 2218.81     653 2196.56   682.9 2186.12   750.2 2188.88
   765.2 2189.88   837.3 2199.81     917 2200.85  1051.9  2209.2  1106.8 2206.53
  1266.7 2221.34  1321.6 2222.38  1376.6 2233.51  1461.5  2236.4  1531.5 2255.09
#Mann= 3 , 0 , 0
       0      .1       0   750.2    .045       0   765.2      .1       0
Bank Sta=750.2,765.2
XS Rating Curve= 0 ,0
Exp/Cntr=0.3,0.1

Type RM Length L Ch R = 1 ,30062.1 ,309.6,315.5,321.3
XS GIS Cut Line= 4
     1873263.271      169003.642     1873646.716      169208.146
     1874247.446      169713.016     1874931.257      170019.772
#Sta/Elev= 30
       0 2547.94   179.8    2484   319.7  2451.6   369.6  2417.7   404.6 2362.36
   419.6  2349.7   444.6 2342.69   534.5 2342.92   584.5 2303.38   624.5 2296.55
   704.5  2243.1   754.4 2232.54   819.4 2187.34   875.5 2185.91   884.4 2185.51
   890.5 2187.35   939.4 2215.91   964.4  2220.2  1034.4    2262  1089.3 2273.92
  1114.3 2290.12  1154.3 2303.33  1209.3 2314.33  1239.3 2314.13  1314.2  2299.8
  1484.1 2333.08    1599 2317.92    1669 2321.36  1788.9 2362.09  1968.7 2365.39
#Mann= 3 , 0 , 0
       0      .1       0   875.5    .045       0   890.5      .1       0
Bank Sta=875.5,890.5
XS Rating Curve= 0 ,0
Exp/Cntr=0.3,0.1

Type RM Length L Ch R = 1 ,29746.6 ,301,300.4,299.8
XS GIS Cut Line= 4
      1873243.96      169271.046     1873664.776      169537.079
      1873896.95      169880.503     1874361.298      170238.438
#Sta/Elev= 30
       0 2461.99    99.6 2461.38   149.4 2451.17   204.1 2417.52   248.9 2360.32
   273.8 2343.78   288.8 2337.96   368.4 2339.54   418.2 2304.56     468 2289.91
   547.8 2239.25   582.8 2230.43   612.7 2200.87   652.7 2182.42   655.4 2182.74
   670.4 2184.62   702.6 2194.95   747.6 2219.12   772.6 2221.54   802.5  2236.8
   832.5 2243.19   857.5 2257.12   917.4 2278.33  1016.7 2334.54  1096.2 2337.89
  1145.9 2375.38  1235.4 2430.49  1319.8 2470.75  1458.9  2510.7  1498.7 2510.74
#Mann= 3 , 0 , 0
       0      .1       0   655.4    .045       0   670.4      .1       0
Bank Sta=655.4,670.4
XS Rating Curve= 0 ,0
Exp/Cntr=0.3,0.1

Type RM Length L Ch R = 1 ,29446.2 ,261.5,258.6,255.7
XS GIS Cut Line= 4
     1873156.895      169416.155     1873495.482      169793.438
     1873713.145      170098.166     1874138.798      170422.243
#Sta/Elev= 30
       0 2376.22    29.8 2362.28    64.6 2357.92    89.5 2344.41   119.3 2340.97
   144.1 2345.01     169 2336.94   238.6 2336.57   263.4 2330.43   372.8 2291.02
   397.6 2286.19   541.9 2212.95   636.8 2182.57   644.7 2182.75   659.7 2184.92
   721.6 2217.62   746.6 2223.02   801.5 2253.05   856.4 2273.42   906.4 2300.41
   946.4 2327.43   971.4 2331.37  1001.4 2329.95  1031.4 2338.78  1066.4 2338.95
  1161.4 2374.11  1291.4 2448.33  1321.4  2463.5  1371.4  2481.5  1416.4 2508.62
#Mann= 3 , 0 , 0
       0      .1       0   644.7    .045       0   659.7      .1       0
Bank Sta=644.7,659.7
XS Rating Curve= 0 ,0
Exp/Cntr=0.3,0.1

Type RM Length L Ch R = 1 ,29187.6 ,329.5,329,328.5
XS GIS Cut Line= 4
     1873032.222      169441.266      1873132.71      169793.438
     1873548.688      170252.949      1873635.06      170676.506
#Sta/Elev= 30
       0 2449.52    64.3 2418.38   128.7  2393.4     193 2345.52   252.4 2327.56
   321.7 2325.67   366.2 2320.63   456.2 2281.11   486.2 2276.67   541.2 2241.18
   681.1  2189.2   706.4 2182.47   716.1 2181.42   721.4 2181.52   736.1 2185.09
   771.1 2209.91   806.1 2218.12   826.1 2231.21   901.1 2268.52   936.1  2290.1
   981.1 2323.82  1090.4 2325.42  1120.2 2354.14  1135.1 2371.32  1140.1 2373.54
    1155  2359.7  1184.8 2344.61  1219.6 2332.04  1254.4 2324.51  1418.3  2324.6
#Mann= 3 , 0 , 0
       0      .1       0   706.4    .045       0   721.4      .1       0
Bank Sta=706.4,721.4
XS Rating Curve= 0 ,0
Exp/Cntr=0.3,0.1

Type RM Length L Ch R = 1 ,28858.6 ,409.7,408.3,406.9
XS GIS Cut Line= 4
     1872633.827      169542.555     1872846.654      169968.208
     1873243.284      170374.512     1873702.796      170814.676
#Sta/Elev= 30
       0 2567.04   198.3 2510.04   282.6  2462.8   312.3 2452.04   366.8 2416.84
   411.4 2355.84   436.2 2334.57   480.9 2321.59   525.7  2326.5   540.6 2322.98
   605.4 2277.48   650.2 2270.01   724.9 2217.24   784.7 2184.85   807.9 2181.42
   814.6  2181.3   822.9 2181.62   884.3 2188.28   924.2 2207.28     959 2210.92
  1008.8 2234.29  1048.7 2244.18    1158 2259.52  1232.6 2260.58  1267.4 2266.52
  1356.9 2304.53  1406.6 2311.63  1441.4 2323.28  1645.2 2325.55    1680 2342.34
#Mann= 3 , 0 , 0
       0      .1       0   807.9    .045       0   822.9      .1       0
Bank Sta=807.9,822.9
XS Rating Curve= 0 ,0
Exp/Cntr=0.3,0.1

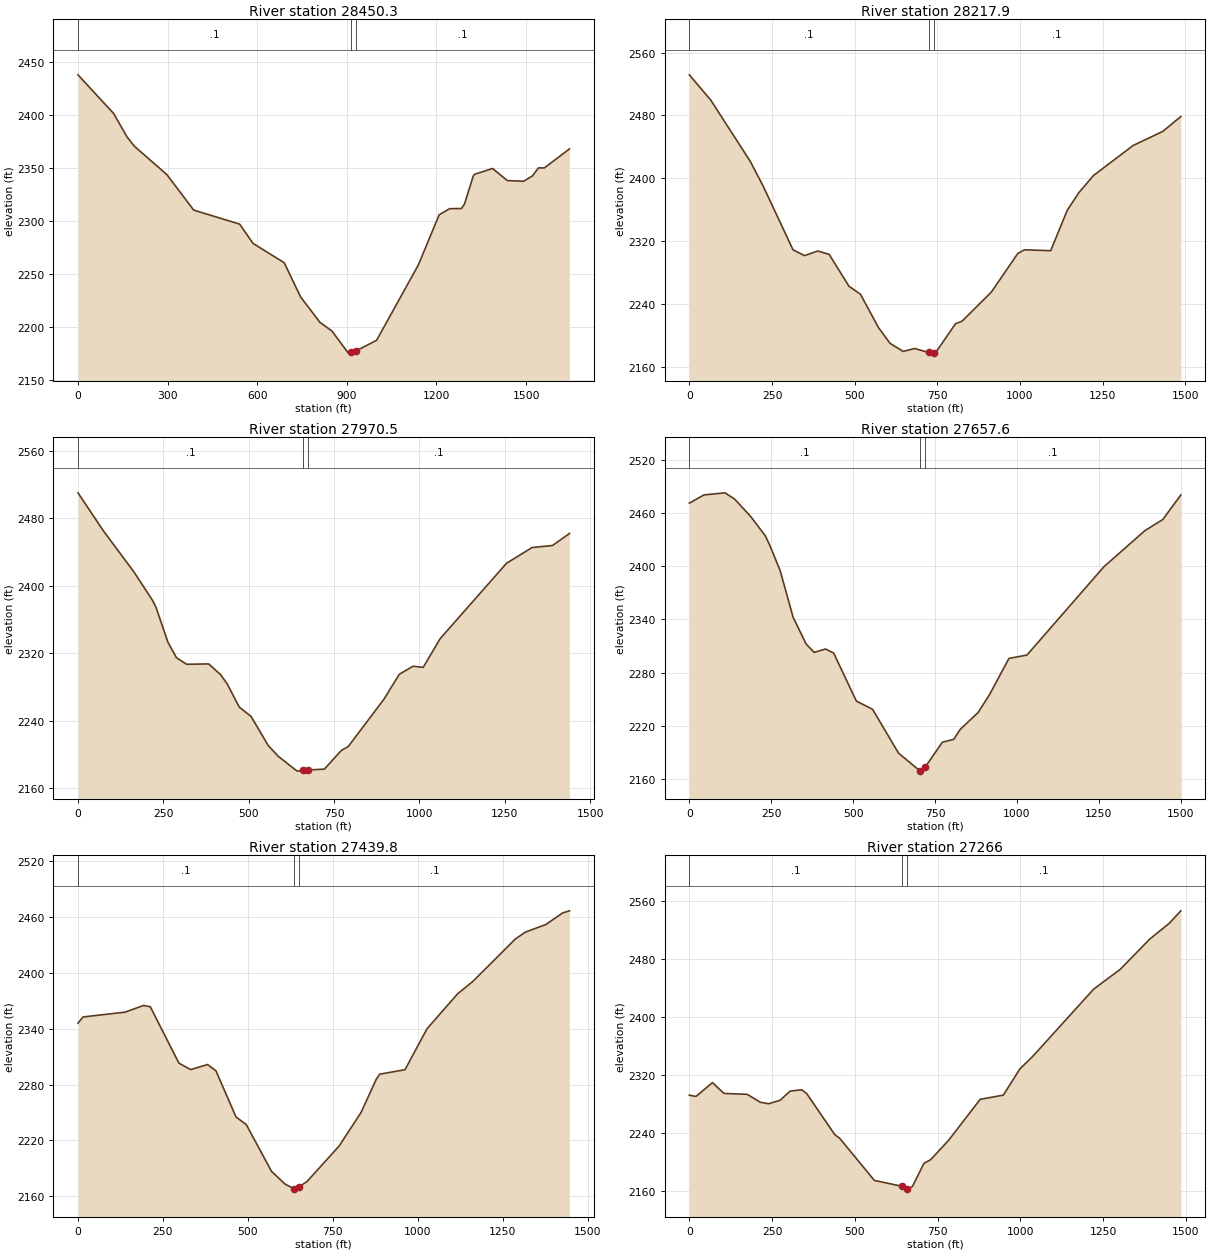
Type RM Length L Ch R = 1 ,28450.3 ,221.2,232.5,243.8
XS GIS Cut Line= 4
     1872334.611      169730.557     1872605.481      170310.993
     1873081.267      170744.074     1873393.906      170925.287
#Sta/Elev= 30
       0 2437.61   119.2  2401.2   163.9 2379.16   188.7 2370.32   297.9 2343.41
   387.3 2310.06   541.2 2296.83   585.9 2278.65   690.4 2260.42   745.3  2228.1
   810.1 2204.17     850 2196.08   904.9 2175.18   914.4 2176.05   929.4 2177.03
   999.6 2187.29  1139.3 2258.29  1209.1 2305.66    1244 2311.38  1283.9 2311.58
  1293.8  2315.8  1323.5 2342.47  1328.4 2343.89  1387.9 2349.29  1437.4 2337.87
  1491.8 2337.22  1521.5 2342.34  1541.3 2349.85  1561.1 2349.83  1645.3 2367.75
#Mann= 3 , 0 , 0
       0      .1       0   914.4    .045       0   929.4      .1       0
Bank Sta=914.4,929.4
XS Rating Curve= 0 ,0
Exp/Cntr=0.3,0.1

Type RM Length L Ch R = 1 ,28217.9 ,245.4,247.4,245.7
XS GIS Cut Line= 4
      1872145.97      170132.025     1872615.155      170562.515
     1872707.057       170823.71     1873161.732      171171.972
#Sta/Elev= 30
       0  2531.7    64.7 2499.63   184.1 2421.81   223.9  2389.7   313.4 2309.34
   348.2 2301.82     388  2307.7   422.8  2303.5   482.5 2263.04   517.4 2252.75
   572.1 2210.32   606.9 2190.38   646.6 2180.06   681.2 2183.75   723.4 2178.77
   735.6 2177.88   738.4 2178.21   750.5 2181.96   804.9 2215.21   824.6 2218.48
   913.6  2255.6   993.3 2304.58  1013.2 2309.23  1092.9 2308.13  1142.7 2359.34
  1177.6 2381.68  1222.4 2403.75    1342 2441.83  1431.6 2459.72  1486.4 2478.68
#Mann= 3 , 0 , 0
       0      .1       0   723.4    .045       0   738.4      .1       0
Bank Sta=723.4,738.4
XS Rating Curve= 0 ,0
Exp/Cntr=0.3,0.1

Type RM Length L Ch R = 1 ,27970.5 ,324.3,312.9,305.1
XS GIS Cut Line= 4
     1872015.372      170301.319     1872363.633      170683.439
     1872716.731      171022.026     1873069.829      171273.548
#Sta/Elev= 30
       0 2510.39    74.6 2465.21     164 2416.57   218.7  2382.7   228.7 2374.51
   263.5 2333.21   288.3 2314.98   318.2 2307.12   382.8 2307.54   417.6 2294.91
   437.5 2283.58   472.3 2256.43   507.1 2245.21     557 2210.96   586.9 2197.92
   641.8 2180.45   658.5 2181.57   673.5 2181.85   721.7  2182.8   771.6 2205.06
   791.6 2209.56   896.4 2265.84   941.3 2295.33   981.3  2304.8  1011.2  2303.5
    1061 2337.58  1255.4 2426.94  1330.1 2445.53  1389.9 2447.93  1439.7 2462.22
#Mann= 3 , 0 , 0
       0      .1       0   658.5    .045       0   673.5      .1       0
Bank Sta=658.5,673.5
XS Rating Curve= 0 ,0
Exp/Cntr=0.3,0.1

Type RM Length L Ch R = 1 ,27657.6 ,223,217.8,216.8
XS GIS Cut Line= 4
     1871757.758      170558.841     1872141.133      170847.895
     1872470.046      171225.178      1872924.72        171476.7
#Sta/Elev= 30
       0 2471.17    44.6 2480.46   108.9  2482.8   138.6 2475.63   188.1 2455.75
   232.6 2433.93   247.5 2422.02   277.2 2395.03   316.8 2342.41   356.4 2312.33
   381.1 2302.84   415.8 2306.63   440.5 2302.11   509.9 2247.88   559.4 2238.59
   638.7 2189.11   704.1 2169.16   708.1 2168.87   719.1 2173.03   772.5 2201.54
   807.2 2204.75     827 2216.08   881.6 2235.03   916.2 2255.09   975.7 2296.03
  1030.6 2299.81  1265.4 2399.39  1390.4  2440.1  1445.3 2452.74  1500.3 2480.42
#Mann= 3 , 0 , 0
       0      .1       0   704.1    .045       0   719.1      .1       0
Bank Sta=704.1,719.1
XS Rating Curve= 0 ,0
Exp/Cntr=0.3,0.1

Type RM Length L Ch R = 1 ,27439.8 ,171.4,173.8,176.3
XS GIS Cut Line= 4
     1871638.089      170765.667     1871991.187      171060.722
     1872382.981      171341.265     1872852.166       171525.07
#Sta/Elev= 30
       0 2345.96    14.8 2352.62   138.5 2357.79     193 2365.01   212.8 2363.55
   296.9 2302.98   331.5 2296.04     381 2301.48   405.7 2294.82   465.1 2244.99
   494.9    2237   569.4 2186.63   609.2 2172.96   635.6 2167.95     639 2167.56
   650.6  2170.2   673.8 2175.72   768.2 2213.92   832.7 2249.95   877.4 2285.59
   887.4 2291.13     962 2295.92  1026.8 2339.96  1116.6 2377.41  1161.6 2390.84
  1286.3 2436.31  1316.2 2443.83  1376.1 2451.95    1426 2464.48  1445.9  2466.7
#Mann= 3 , 0 , 0
       0      .1       0   635.6    .045       0   650.6      .1       0
Bank Sta=635.6,650.6
XS Rating Curve= 0 ,0
Exp/Cntr=0.3,0.1

Type RM Length L Ch R = 1 ,27266   ,265.7,260.8,255.6
XS GIS Cut Line= 4
     1871517.165      170993.004     1871889.611      171162.298
     1872324.937      171544.418     1872779.612      171742.733
#Sta/Elev= 30
       0 2292.54      20 2290.75    69.8 2309.82   104.8 2294.87   174.6 2293.67
   214.5 2282.72   239.5 2280.68   274.4 2285.58   304.3 2298.12   339.3 2299.98
   354.2 2294.88   439.1 2238.23   454.1 2233.06   558.9 2174.94   643.3 2166.81
   658.3 2163.12   658.8 2162.96   673.8 2166.66   708.7 2198.57   728.7 2203.52
   783.6 2230.58   878.5 2286.82   948.4 2292.58   998.3 2328.76    1038 2346.42
  1221.5 2438.91  1300.9  2465.8  1390.2 2507.59  1449.7 2529.62  1484.4 2546.68
#Mann= 3 , 0 , 0
       0      .1       0   643.3    .045       0   658.3      .1       0
Bank Sta=643.3,658.3
XS Rating Curve= 0 ,0
Exp/Cntr=0.3,0.1

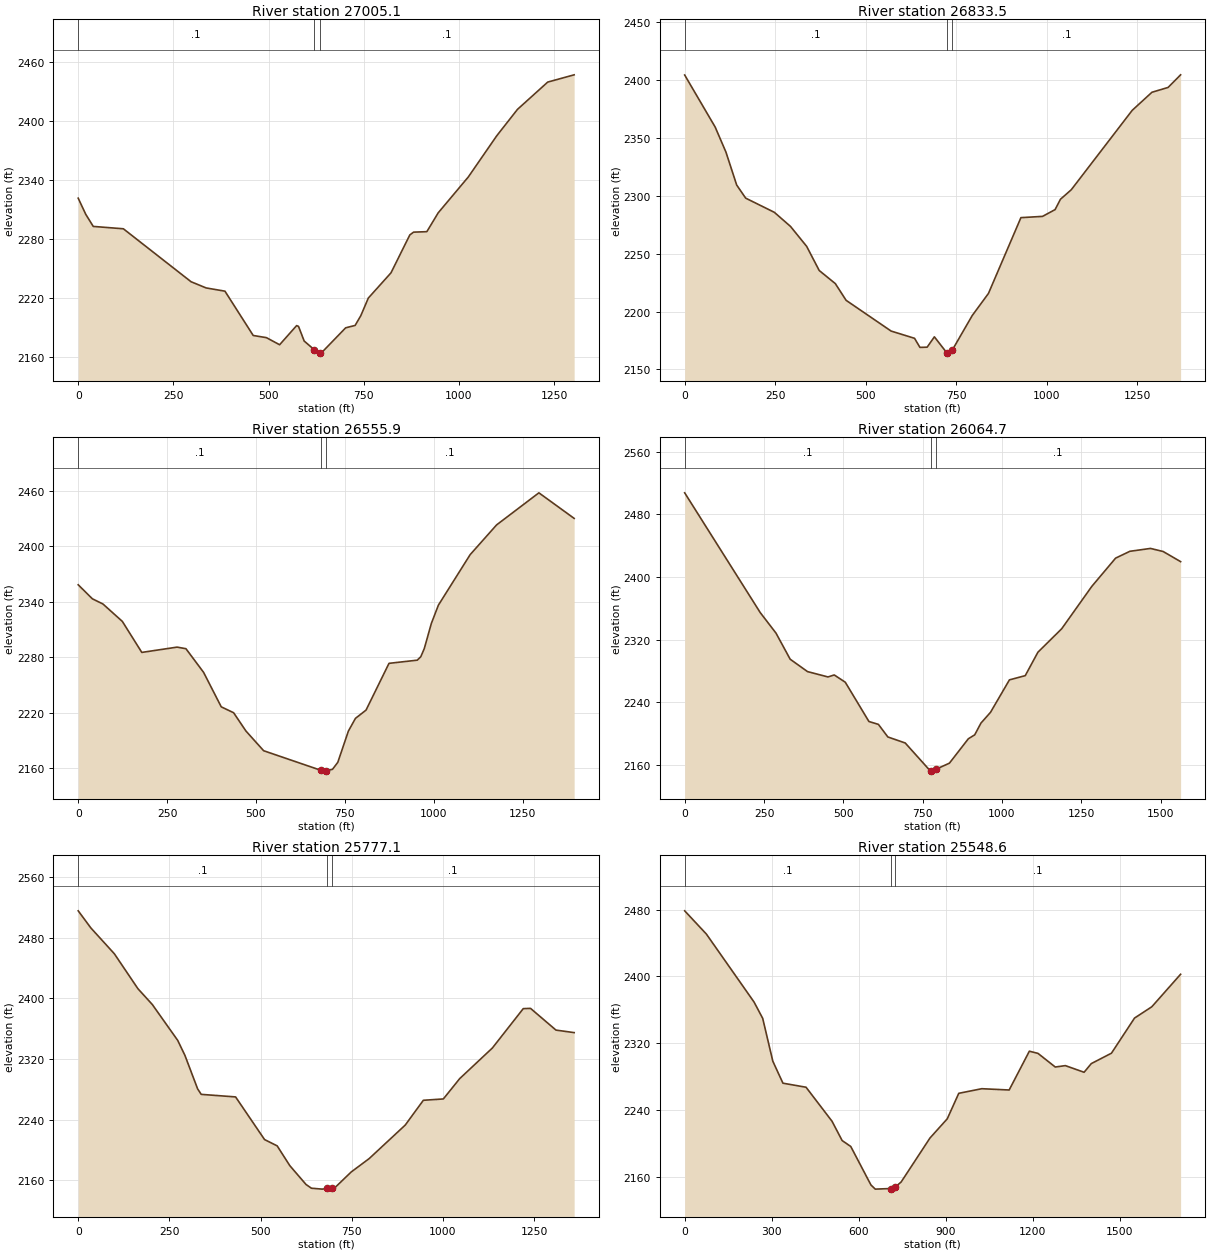
Type RM Length L Ch R = 1 ,27005.1 ,174.8,171.6,169
XS GIS Cut Line= 4
     1871434.936      171162.298      1871763.85      171423.494
     1872170.155      171641.157     1872505.212      171897.196
#Sta/Elev= 30
       0 2321.51    19.8 2305.08    39.5 2292.74   118.6 2290.32   296.5 2236.32
     336 2230.02   385.4 2226.72   459.7 2181.54   494.4 2179.33     529  2172.1
   573.6  2191.6   578.6 2190.87   593.5  2175.9   619.7 2167.13   634.7 2163.99
   638.1 2163.56   702.5 2189.37   727.3 2191.79   742.2 2201.71     762  2219.7
   821.5  2245.4     871 2284.06   880.9 2286.91   915.7 2287.38   945.4 2306.52
  1024.8 2343.25  1099.2 2385.09  1153.8 2412.08  1233.2 2439.88  1302.6 2447.28
#Mann= 3 , 0 , 0
       0      .1       0   619.7    .045       0   634.7      .1       0
Bank Sta=619.7,634.7
XS Rating Curve= 0 ,0
Exp/Cntr=0.3,0.1

Type RM Length L Ch R = 1 ,26833.5 ,266.5,277.6,288.5
XS GIS Cut Line= 4
     1871226.947      171389.635     1871676.785      171597.624
     1872136.296      171776.592      1872431.35       172018.44
#Sta/Elev= 30
       0 2404.56    84.2 2359.58     114  2337.9   143.7  2309.4   168.5 2298.08
   247.8 2285.79   292.4  2273.6     337 2256.37   371.7 2235.49   416.3 2224.12
     446  2209.7   570.3 2183.11   635.1 2176.83     650 2168.98   669.9 2169.17
   689.9 2178.11   724.3 2164.25   729.7 2164.02   739.3 2166.63   794.5 2196.55
   839.3 2215.64     929  2281.2   988.7 2282.29  1023.4 2288.16  1038.3 2297.13
    1068 2305.29  1236.5 2374.02    1291 2389.64  1335.6 2393.81  1370.2 2404.72
#Mann= 3 , 0 , 0
       0      .1       0   724.3    .045       0   739.3      .1       0
Bank Sta=724.3,739.3
XS Rating Curve= 0 ,0
Exp/Cntr=0.3,0.1

Type RM Length L Ch R = 1 ,26555.9 ,504.4,491.3,477.8
XS GIS Cut Line= 4
     1871135.045      171544.418     1871551.024      171694.364
     1871870.263      172061.973     1872242.709      172342.516
#Sta/Elev= 30
       0 2358.35    39.8 2343.17    69.6 2337.53   124.2 2318.67   178.9  2285.1
   278.2 2290.82   303.1 2289.11   352.8 2263.46   402.4 2226.16   437.2 2219.76
     472 2199.91   521.7 2178.62   682.6 2157.43   690.6 2156.52   697.6 2156.73
   715.4 2158.48   730.3    2166   760.1 2199.86     780 2213.66   809.8 2222.61
   874.4 2273.26   953.9  2276.7   963.8  2280.4   973.7 2289.28   993.5 2316.45
  1013.4 2336.31  1102.7 2390.97  1177.1 2423.19  1296.1 2457.94  1395.3 2430.26
#Mann= 3 , 0 , 0
       0      .1       0   682.6    .045       0   697.6      .1       0
Bank Sta=682.6,697.6
XS Rating Curve= 0 ,0
Exp/Cntr=0.3,0.1

Type RM Length L Ch R = 1 ,26064.7 ,285.8,287.5,289.6
XS GIS Cut Line= 4
     1870810.969      171828.978     1871251.132      172143.381
     1871754.176      172264.305     1872247.546      172370.718
#Sta/Elev= 30
       0 2507.41   238.2 2354.49   287.8 2328.31   332.5 2294.99   387.1  2279.2
   451.6 2272.36   471.4 2274.91   506.2  2265.6   580.7 2215.48   610.6  2211.8
   640.4 2195.72   695.1 2188.06   774.7 2152.13   775.8 2152.14   790.8 2154.29
   834.4  2162.3   894.1 2193.48     914 2198.43   933.9 2213.54   963.8 2227.17
  1023.5 2268.63  1073.3 2274.02  1113.3 2303.94  1188.2 2333.87  1283.2 2388.01
  1358.1 2424.03  1403.1 2432.76  1468.1 2436.43    1508  2432.5    1563 2419.56
#Mann= 3 , 0 , 0
       0      .1       0   775.8    .045       0   790.8      .1       0
Bank Sta=775.8,790.8
XS Rating Curve= 0 ,0
Exp/Cntr=0.3,0.1

Type RM Length L Ch R = 1 ,25777.1 ,230.2,228.5,226.8
XS GIS Cut Line= 4
     1870757.762      172216.755      1871222.11      172390.886
     1871623.578      172531.158     1872054.068      172613.386
#Sta/Elev= 30
       0 2515.42    34.7 2492.84    99.2 2458.72   163.6 2412.78   203.3 2391.79
   272.8 2344.55   292.6 2324.75   327.3 2280.69   337.2 2273.39   431.4 2270.03
   510.8 2213.81   545.4 2205.48     580 2179.44   624.5 2154.56   639.3 2149.63
     669 2148.44   681.3 2149.31   696.3 2149.85   703.6 2150.34   748.1 2170.95
   797.6 2188.71   896.5 2232.92   946.1 2265.59  1000.9 2267.34  1045.7 2294.12
  1135.4 2334.56    1220 2386.45  1239.9 2386.79  1309.7 2358.14  1359.5 2354.82
#Mann= 3 , 0 , 0
       0      .1       0   681.3    .045       0   696.3      .1       0
Bank Sta=681.3,696.3
XS Rating Curve= 0 ,0
Exp/Cntr=0.3,0.1

Type RM Length L Ch R = 1 ,25548.6 ,409.8,422.3,434.8
XS GIS Cut Line= 4
     1870762.599      172318.332     1871154.393      172618.223
     1871691.295      172763.332     1872349.122      172826.212
#Sta/Elev= 30
       0 2478.59    74.8 2450.77   239.2 2369.37   269.1 2349.76     304 2298.45
   338.9 2272.11   418.6 2267.26   508.3 2226.48     543 2203.42   572.8  2196.3
   642.4 2150.21   657.3 2145.21   710.9 2145.92   725.9  2147.6   746.6 2153.78
     846 2206.44   905.6 2229.44   945.3 2259.97  1024.7  2265.5  1119.1 2263.95
  1188.7 2310.42  1218.5 2307.82  1278.1 2291.48  1312.9 2293.16  1377.5  2285.2
  1402.3 2295.57  1471.9 2308.05  1551.4  2350.1    1611 2363.64  1710.4 2402.61
#Mann= 3 , 0 , 0
       0      .1       0   710.9    .045       0   725.9      .1       0
Bank Sta=710.9,725.9
XS Rating Curve= 0 ,0
Exp/Cntr=0.3,0.1