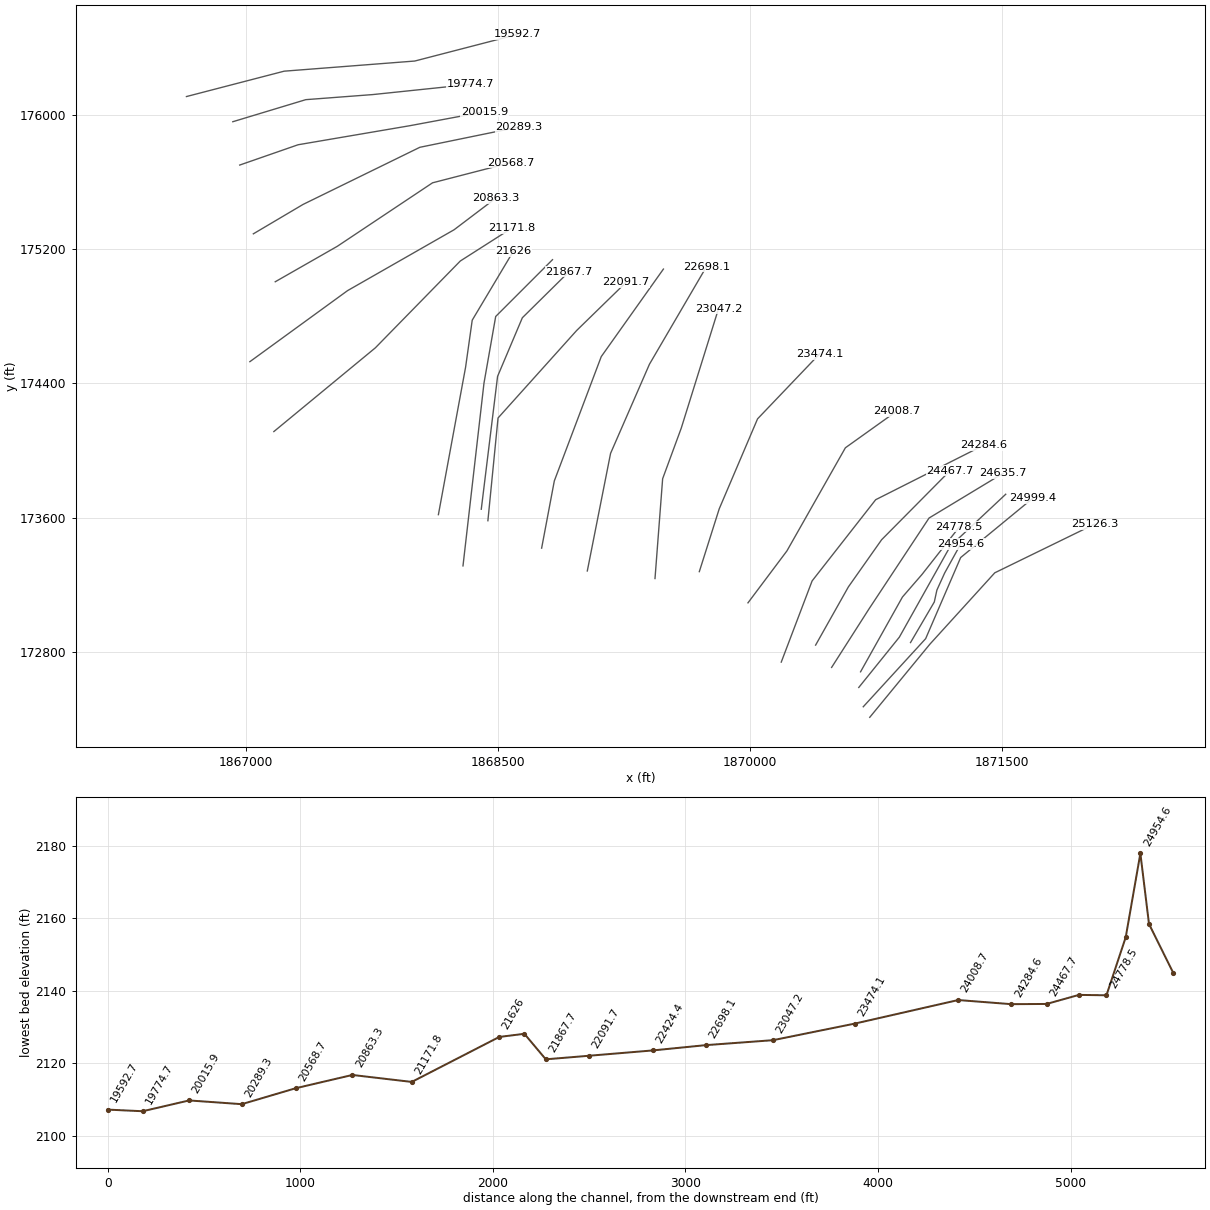
HEC-RAS study BeartownFk.prj: BeartownFk

--- BeartownFk.g01 (geometry) --- (continued)

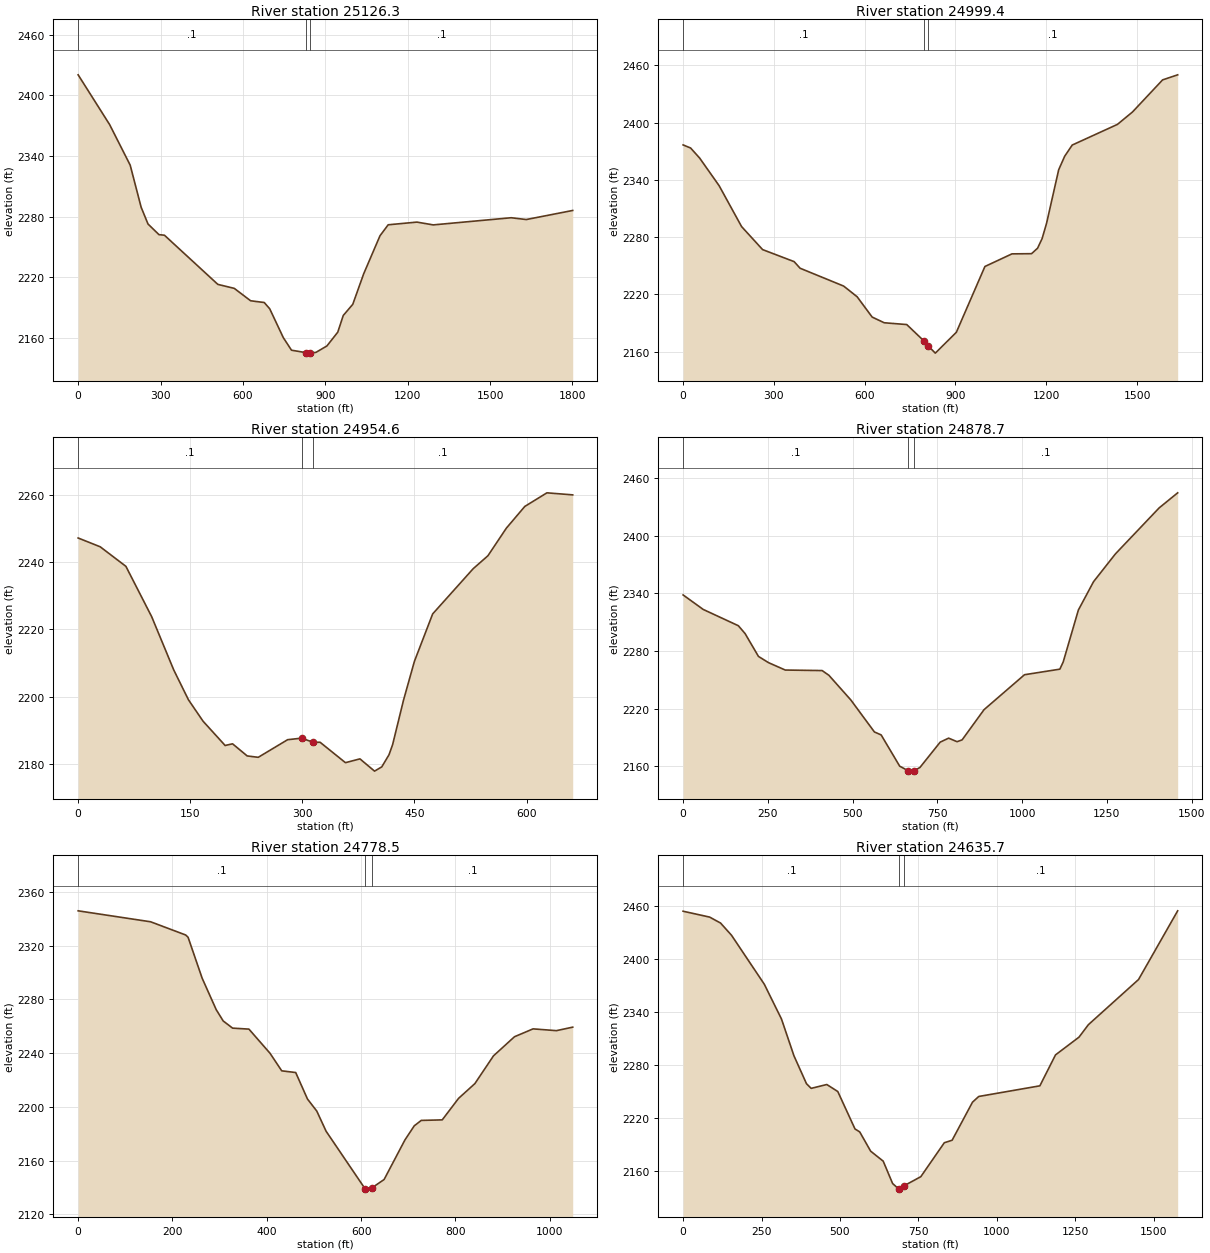
Type RM Length L Ch R = 1 ,25126.3 ,119.4,126.9,134.4
XS GIS Cut Line= 4
     1870714.229      172410.234     1871072.164       172845.56
     1871459.121      173271.213     1872054.068      173561.431
#Sta/Elev= 30
       0  2420.3   114.7 2371.03   189.5 2330.93   229.4 2289.26   254.4 2272.65
   294.3 2262.14   314.2 2261.56   508.7  2212.9   568.5 2208.96     628 2196.69
   677.6 2194.95   697.5 2188.78   747.1 2160.17   776.8 2147.78   829.7 2145.33
   841.3 2144.87   844.7 2144.95   866.1 2145.65   905.8 2151.97   945.4 2165.64
   965.3 2182.13    1000 2193.19  1039.6 2223.32  1099.2 2261.07  1128.9 2271.88
  1233.4 2274.54  1293.1 2271.78  1576.8 2278.86  1631.6 2277.07  1800.8 2286.06
#Mann= 3 , 0 , 0
       0      .1       0   829.7    .045       0   844.7      .1       0
Bank Sta=829.7,844.7
XS Rating Curve= 0 ,0
Exp/Cntr=0.3,0.1

Type RM Length L Ch R = 1 ,24999.4 ,40.5,44.8,49.2
XS GIS Cut Line= 4
     1870675.534      172473.114     1871047.285       172878.77
       1871255.9      173362.173     1871686.458      173716.213
#Sta/Elev= 30
       0 2376.73    24.8 2373.48    54.5 2363.02     119    2334   193.3  2291.1
   262.7 2266.99   366.8 2254.39   386.6 2247.45   530.4 2228.78   575.1 2217.54
   624.7 2196.26   664.5  2190.3     739 2188.41   795.5 2171.32   810.5 2165.76
   833.4 2158.47   902.9 2180.32   997.3 2249.29  1086.7 2262.52  1151.4 2262.71
  1171.3 2268.46  1186.2 2278.49  1201.2 2294.83    1241 2350.65  1260.9 2364.89
  1285.8 2376.59  1435.1 2398.23  1484.8 2411.22  1584.4 2444.89  1634.2  2450.2
#Mann= 3 , 0 , 0
       0      .1       0   795.5    .045       0   810.5      .1       0
Bank Sta=795.5,810.5
XS Rating Curve= 0 ,0
Exp/Cntr=0.3,0.1

Type RM Length L Ch R = 1 ,24954.6 ,101.7,75.9,69
XS GIS Cut Line= 5
      1870957.16      172855.609     1871098.893       173097.48
     1871114.299      173168.347     1871160.516      173270.025
     1871256.032       173442.57
#Sta/Elev= 30
       0 2247.16    29.5 2244.55    63.9 2238.75    98.4  2223.8   127.9    2208
   147.6 2199.13   167.2 2192.76   196.7 2185.56   206.6 2186.06   226.2 2182.46
     241 2182.05   280.3 2187.28   299.2 2187.74   314.2 2186.52   323.8 2186.51
   357.7 2180.46   377.1 2181.59   396.6 2177.95   406.3 2179.21     416 2182.82
   420.8 2185.81   435.4 2199.02     450 2210.56   474.4 2224.62   528.6 2238.04
   548.4  2241.9     573 2250.08   597.7 2256.53   627.3 2260.57   661.8 2259.96
#Mann= 3 , 0 , 0
       0      .1       0   299.2    .045       0   314.2      .1       0
Bank Sta=299.2,314.2
XS Rating Curve= 0 ,0
Exp/Cntr=0.3,0.1

Type RM Length L Ch R = 1 ,24878.7 ,106.3,100.2,110.7
XS GIS Cut Line= 4
     1870648.853      172588.108     1870890.701         172888.
     1871194.609      173430.434     1871524.343      173739.305
#Sta/Elev= 30
       0 2338.36    59.3 2323.25     163 2306.29   182.8 2298.12   222.3 2274.32
   251.9 2267.84   301.3 2260.13   410.1 2259.58     430 2254.68   494.7 2228.99
   564.3 2195.65   584.2 2192.54   638.9    2160   664.8 2155.06   673.8 2154.85
   679.8 2154.95   698.6 2158.66   758.3 2185.04   783.2  2189.2   808.1  2185.5
     823  2187.4   887.6 2218.84    1007 2255.25  1111.3 2261.05  1121.2 2268.58
  1165.9 2322.61  1210.6 2352.13  1275.1 2381.06  1404.2 2429.01  1458.8  2444.7
#Mann= 3 , 0 , 0
       0      .1       0   664.8    .045       0   679.8      .1       0
Bank Sta=664.8,679.8
XS Rating Curve= 0 ,0
Exp/Cntr=0.3,0.1

Type RM Length L Ch R = 1 ,24778.5 ,139.9,142.8,145.8
XS GIS Cut Line= 4
      1870659.52       172681.31     1870909.228      173127.217
     1871025.164       173260.99     1871248.118      173544.587
#Sta/Elev= 30
       0 2345.84   153.8 2337.68   228.2 2327.84   233.2 2326.11     263 2295.69
   292.8 2272.32   307.6  2263.9   327.5 2258.57   362.2 2257.83   406.9 2239.87
   431.7  2226.8   461.4 2225.53   486.3 2205.84   506.1 2196.84   525.8 2181.88
   608.4 2139.09   609.4 2138.79   623.4 2139.82   648.8 2145.93     693 2175.38
   712.8 2185.89   727.6 2189.91   772.1 2190.31   806.7  2206.3   841.3 2217.28
   880.8 2237.95   925.3 2252.16   964.8 2258.02  1014.2 2256.69  1048.8 2259.29
#Mann= 3 , 0 , 0
       0      .1       0   608.4    .045       0   623.4      .1       0
Bank Sta=608.4,623.4
XS Rating Curve= 0 ,0
Exp/Cntr=0.3,0.1

Type RM Length L Ch R = 1 ,24635.7 ,168.7,168,167.3
XS GIS Cut Line= 4
     1870487.061       172707.51     1870709.561      173055.771
     1871067.496      173597.511     1871507.659      173863.544
#Sta/Elev= 30
       0 2453.85    84.6 2447.21   119.5 2440.44   154.4  2426.6   258.9 2371.12
   313.7 2331.68   353.5 2289.96   393.4 2258.37   408.3  2253.1   458.2 2257.47
   493.2 2249.51   548.1 2207.08   563.1 2203.77   598.1 2181.88     638 2170.62
     668 2145.26     688  2138.9   689.8 2138.95   704.8 2142.76   757.9    2153
   832.8 2191.46   857.8 2194.33   922.7 2237.44   942.7 2243.91  1137.5 2255.97
  1187.4 2291.03  1262.3 2311.14  1292.3 2325.29  1452.1 2376.44  1576.9 2454.31
#Mann= 3 , 0 , 0
       0      .1       0   689.8    .045       0   704.8      .1       0
Bank Sta=689.8,704.8
XS Rating Curve= 0 ,0
Exp/Cntr=0.3,0.1

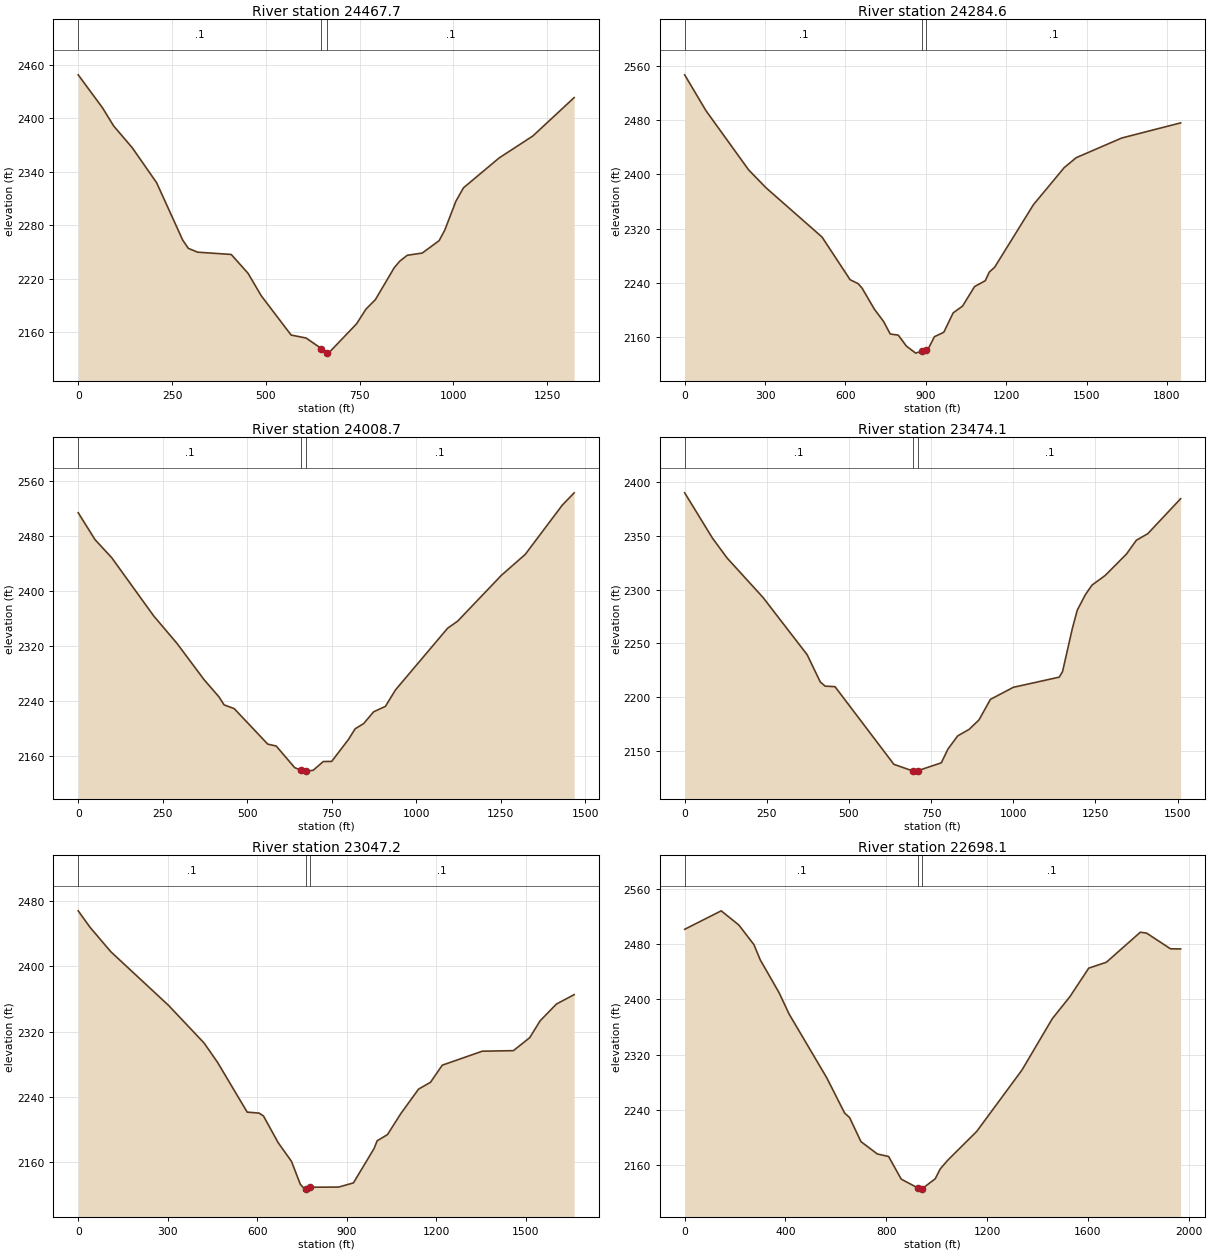
Type RM Length L Ch R = 1 ,24467.7 ,184.4,183.1,181.8
XS GIS Cut Line= 4
     1870391.711      172840.503      1870586.91        173187.2
     1870785.022      173468.345     1871193.071       173880.07
#Sta/Elev= 30
       0 2449.06    64.6 2412.09    94.5 2391.62   144.2 2367.05   208.9 2327.88
   278.5 2263.35   293.4 2254.12   318.3 2249.82   407.8 2247.25   452.7    2226
   487.6 2200.94   567.4  2156.7   607.2 2153.38   647.8 2141.58   662.8 2136.65
     667  2136.4   741.8 2169.35   766.8 2185.84   791.8 2196.49   841.8 2232.18
   856.7 2239.66   876.7 2246.33   916.7 2248.82   961.7 2262.74   976.7 2274.57
  1006.7 2307.33  1026.6 2322.12  1121.6 2355.67  1211.5 2380.38  1321.5 2423.48
#Mann= 3 , 0 , 0
       0      .1       0   647.8    .045       0   662.8      .1       0
Bank Sta=647.8,662.8
XS Rating Curve= 0 ,0
Exp/Cntr=0.3,0.1

Type RM Length L Ch R = 1 ,24284.6 ,272.2,275.9,279.7
XS GIS Cut Line= 4
        1870187.      172739.147     1870370.805      173222.843
     1870749.513       173706.68     1871391.404      174030.616
#Sta/Elev= 30
       0 2547.08    79.6  2494.1   238.8 2406.74   303.5 2380.41   512.5 2307.74
   617.4 2244.71   647.3 2238.91   662.3 2232.13   707.3 2201.64   742.2  2183.1
   767.2 2164.59   797.2  2162.9   827.2 2146.84   862.1 2136.34   886.9 2139.56
   901.9 2140.89   912.1 2145.13     932 2160.54     967 2167.14    1002 2195.74
    1037 2205.76  1081.9 2234.56  1121.9 2243.25  1136.9 2255.97  1156.8 2263.04
  1301.6 2355.43  1416.5 2410.16  1461.4 2424.85  1631.2 2453.84  1850.9 2476.15
#Mann= 3 , 0 , 0
       0      .1       0   886.9    .045       0   901.9      .1       0
Bank Sta=886.9,901.9
XS Rating Curve= 0 ,0
Exp/Cntr=0.3,0.1

Type RM Length L Ch R = 1 ,24008.7 ,537.7,534.6,549.9
XS GIS Cut Line= 4
     1869988.685      173092.245     1870220.859      173401.811
      1870569.12      174016.105     1870873.849      174233.768
#Sta/Elev= 30
       0 2514.11    49.6 2474.95    99.2 2448.49   223.2  2363.8   292.7  2323.4
   372.1 2270.99   416.8 2245.54   431.7 2234.06   461.6 2228.58     561 2176.79
   585.9 2174.08   640.6 2142.57     660 2138.51     675  2137.5   675.4 2137.48
   695.3  2138.7   725.1 2151.46     750 2151.62   799.7 2183.64   819.6 2199.22
   844.5  2206.7   874.3 2223.97   909.1 2231.86   938.9 2255.84  1093.1 2345.72
  1123.1 2356.16  1252.9 2423.15  1322.8 2453.29  1432.6  2525.2  1467.6 2543.06
#Mann= 3 , 0 , 0
       0      .1       0     660    .045       0     675      .1       0
Bank Sta=660,675
XS Rating Curve= 0 ,0
Exp/Cntr=0.3,0.1

Type RM Length L Ch R = 1 ,23474.1 ,425.8,426.9,427.9
XS GIS Cut Line= 4
     1869698.809      173278.132     1869817.426      173652.426
     1870045.747       174188.35     1870414.489      174574.472
#Sta/Elev= 30
       0 2390.15    84.5 2347.99   129.2 2329.41   238.6 2292.65   372.8 2239.36
   412.6 2214.04   427.5 2210.14   457.4 2209.67   636.6 2137.33   695.1 2131.07
   696.4    2131   710.1 2131.46     781 2138.76   800.9 2151.45   830.8 2163.82
   865.6 2169.89   895.5 2178.68   930.4 2197.83  1000.1 2209.05  1139.8 2218.53
  1149.8 2223.68  1179.8 2264.02  1194.7 2280.96  1219.7 2295.55  1239.6 2304.26
  1279.6 2313.21  1344.4 2333.16  1374.4 2345.98  1409.3 2352.12  1509.1 2384.69
#Mann= 3 , 0 , 0
       0      .1       0   695.1    .045       0   710.1      .1       0
Bank Sta=695.1,710.1
XS Rating Curve= 0 ,0
Exp/Cntr=0.3,0.1

Type RM Length L Ch R = 1 ,23047.2 ,350.5,349.1,347.7
XS GIS Cut Line= 4
     1869434.779       173237.07     1869480.301      173831.702
     1869591.261      174133.287     1869813.181       174844.57
#Sta/Elev= 30
       0 2468.33    39.8 2448.03   109.3 2418.11   303.2 2352.04   422.4 2305.76
   467.2 2282.15   566.6    2221   606.3 2219.81   621.1 2216.34   670.5 2183.44
     715 2160.54   744.7 2132.36   759.5  2126.4   762.7 2126.83   777.7 2128.72
   873.2 2128.93   922.7 2134.04   992.2 2176.41  1002.2 2185.77  1036.9 2193.36
  1081.6 2219.18  1141.2  2249.3    1181 2257.62  1220.7 2278.71  1354.8 2295.86
  1459.2 2296.54  1513.8  2312.5  1548.6 2333.13  1603.2 2353.76  1662.8 2365.37
#Mann= 3 , 0 , 0
       0      .1       0   762.7    .045       0   777.7      .1       0
Bank Sta=762.7,777.7
XS Rating Curve= 0 ,0
Exp/Cntr=0.3,0.1

Type RM Length L Ch R = 1 ,22698.1 ,272.5,273.7,274.7
XS GIS Cut Line= 4
      1869031.42      173282.096     1869170.098      173982.851
      1869401.75       174514.01     1869741.849      175095.956
#Sta/Elev= 30
       0 2501.47   144.9 2528.24   214.8 2507.75   274.8 2479.28   299.7  2457.3
   374.7 2409.59   414.6 2378.57   564.5  2285.9   634.4  2235.4   654.4 2228.72
   699.4 2193.89   764.3 2176.01   809.3 2172.28   859.2 2139.52   926.5 2126.49
   939.1 2125.03   941.5 2125.43   994.1 2140.02  1014.1 2154.32    1044 2166.97
  1158.9 2208.68  1338.8 2297.81  1458.6 2371.91  1528.5 2403.81  1603.4 2445.21
  1673.3 2453.76  1808.1 2497.25    1833 2495.95  1927.9 2473.17  1967.9 2473.05
#Mann= 3 , 0 , 0
       0      .1       0   926.5    .045       0   941.5      .1       0
Bank Sta=926.5,941.5
XS Rating Curve= 0 ,0
Exp/Cntr=0.3,0.1

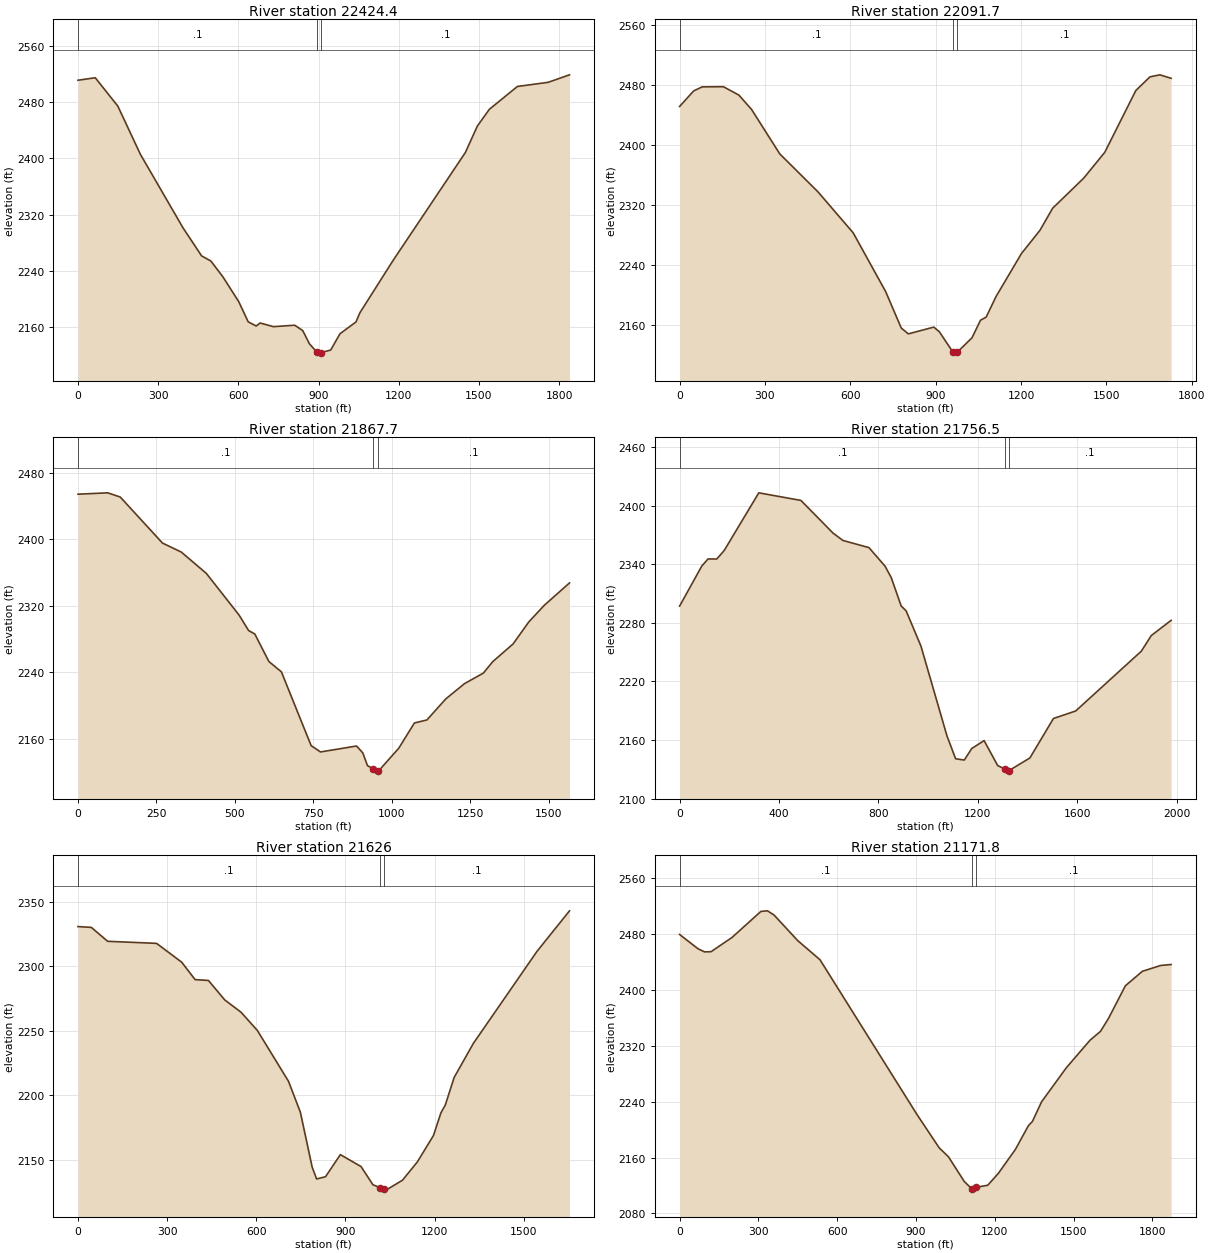
Type RM Length L Ch R = 1 ,22424.4 ,341.2,332.7,324.3
XS GIS Cut Line= 4
     1868759.341      173418.136     1868834.919      173818.696
     1869114.555      174559.356     1869484.885      175080.841
#Sta/Elev= 30
       0 2510.76    64.6 2514.32   149.1 2474.01   233.6 2405.58   392.7  2301.5
   462.4 2261.59   497.2 2254.25   542.1 2231.87   601.8 2196.35   636.7 2168.04
   666.6 2162.06   681.5 2166.32   731.3 2161.15   810.9 2163.18   840.8 2155.56
   865.7 2136.94   894.8 2124.48   900.6 2123.58   909.8 2124.42   945.4 2127.92
   980.2 2151.08    1040 2167.81  1054.9 2180.98  1179.4 2255.41  1449.2 2408.19
  1494.1 2445.72  1539.1 2469.57    1644 2501.94    1759  2507.8  1838.9 2518.45
#Mann= 3 , 0 , 0
       0      .1       0   894.8    .045       0   909.8      .1       0
Bank Sta=894.8,909.8
XS Rating Curve= 0 ,0
Exp/Cntr=0.3,0.1

Type RM Length L Ch R = 1 ,22091.7 ,216.4,224.1,231.7
XS GIS Cut Line= 4
     1868439.158      173581.473      1868499.62      174193.651
     1868968.201      174715.136     1869262.953       175002.33
#Sta/Elev= 30
       0 2451.04    49.6 2471.82    79.4 2477.18   153.8  2477.4   208.4  2466.2
     253 2447.04   352.2 2387.77   486.2 2337.26   610.2 2282.52   724.5 2204.08
   779.2 2155.57   804.1 2147.77   893.6  2156.8   913.5 2150.39   961.5 2123.03
   968.2  2122.1   976.5 2123.54  1027.8 2142.52  1057.7 2165.95  1077.6 2170.11
  1112.4  2197.6  1201.9 2255.03  1266.5 2285.73  1311.3 2315.33  1420.4 2355.38
  1494.7 2389.97  1603.8 2472.35  1653.4 2490.49  1688.1 2493.23  1727.8 2488.61
#Mann= 3 , 0 , 0
       0      .1       0   961.5    .045       0   976.5      .1       0
Bank Sta=961.5,976.5
XS Rating Curve= 0 ,0
Exp/Cntr=0.3,0.1

Type RM Length L Ch R = 1 ,21867.7 ,106.1,111.2,116.3
XS GIS Cut Line= 4
     1868399.743      173650.048     1868496.901      174441.707
     1868644.438      174790.757     1868921.518      175064.239
#Sta/Elev= 30
       0 2454.08    94.7 2455.73   134.6 2450.68   269.2 2395.32     329 2384.53
   408.8 2358.91   513.4 2308.65   543.4 2290.23   563.3 2285.99   608.2 2252.92
     648 2240.49   742.8 2151.76   772.7 2144.17   887.4 2151.32   907.3 2143.09
   922.2 2127.76   941.2 2123.77   956.2 2121.22   957.2 2121.12    1022 2148.71
  1071.8 2179.04  1111.7 2182.66  1171.6 2207.92  1231.4 2226.32  1291.4 2238.98
  1321.3 2252.75  1386.2 2274.06  1436.1 2300.47    1486 2320.67  1565.9 2347.42
#Mann= 3 , 0 , 0
       0      .1       0   941.2    .045       0   956.2      .1       0
Bank Sta=941.2,956.2
XS Rating Curve= 0 ,0
Exp/Cntr=0.3,0.1

Type RM Length L Ch R = 1 ,21756.5 ,129.8,130.5,131.2
XS GIS Cut Line= 4
     1868290.761      173312.327     1868415.829      174401.037
     1868485.652      174798.496      1868824.03      175136.874
#Sta/Elev= 30
       0 2297.11    89.7 2338.29   114.6 2345.41   149.4 2345.32   179.3 2353.95
   318.8 2413.09   488.2 2405.31   617.7 2371.81   657.5  2364.3   762.1 2356.99
   826.9 2337.97   851.8 2326.25   891.6  2297.3   911.6 2292.26   971.3 2256.13
    1076 2164.21  1110.8 2140.83  1145.7  2139.5  1175.6 2151.29  1225.4  2159.4
  1280.2 2133.81  1310.4 2130.21  1320.1 2128.16  1325.4 2128.69  1409.7 2141.64
  1504.4 2182.04  1594.1 2189.76  1858.3 2251.03  1898.2 2266.97    1978 2282.54
#Mann= 3 , 0 , 0
       0      .1       0  1310.4    .045       0  1325.4      .1       0
Bank Sta=1310.4,1325.4
XS Rating Curve= 0 ,0
Exp/Cntr=0.3,0.1

Type RM Length L Ch R = 1 ,21626   ,468.4,454.2,440
XS GIS Cut Line= 4
     1868144.253      173617.662     1868306.184      174495.684
     1868345.766      174776.363     1868590.461      175186.586
#Sta/Elev= 30
       0 2330.71    44.9 2330.09    99.8 2319.31   264.4 2317.71   349.2 2303.07
     394 2289.63   438.9 2288.97   493.8 2273.89   548.7 2264.35   603.5 2250.25
   708.3 2210.86   748.2 2186.95   788.1 2144.23     803 2135.15     833  2136.9
   882.8 2154.03   952.5 2144.76   992.3 2130.71  1015.9 2128.43  1030.9 2127.63
    1042 2127.29  1091.8 2134.19  1141.5 2148.24  1196.2 2168.86  1221.1 2186.35
    1236 2192.48  1265.8 2213.85  1330.5 2240.26  1544.5 2311.52  1653.9 2342.92
#Mann= 3 , 0 , 0
       0      .1       0  1015.9    .045       0  1030.9      .1       0
Bank Sta=1015.9,1030.9
XS Rating Curve= 0 ,0
Exp/Cntr=0.3,0.1

Type RM Length L Ch R = 1 ,21171.8 ,314.8,308.5,302.3
XS GIS Cut Line= 4
     1867163.884      174112.652     1867768.504      174611.464
     1868274.723      175128.899     1868581.095      175324.407
#Sta/Elev= 30
       0 2479.69    69.9  2459.3    94.9 2454.78   119.8 2455.02   199.7 2475.46
   309.5 2512.73   334.5 2513.57   359.5  2507.6   449.3 2471.02   534.2 2443.63
   903.6 2221.82   988.5 2173.88  1023.4 2161.29  1083.4 2125.99  1113.3 2114.88
  1128.3 2117.43  1173.2 2120.47  1213.2 2137.37  1278.1  2171.6    1328 2205.92
    1343 2211.79  1377.9 2239.95  1472.8 2289.06  1562.5 2328.25  1602.3  2340.9
  1632.2 2359.08  1696.9 2406.16  1761.6 2426.91  1831.3  2435.3  1871.1 2436.66
#Mann= 3 , 0 , 0
       0      .1       0  1113.3    .045       0  1128.3      .1       0
Bank Sta=1113.3,1128.3
XS Rating Curve= 0 ,0
Exp/Cntr=0.3,0.1

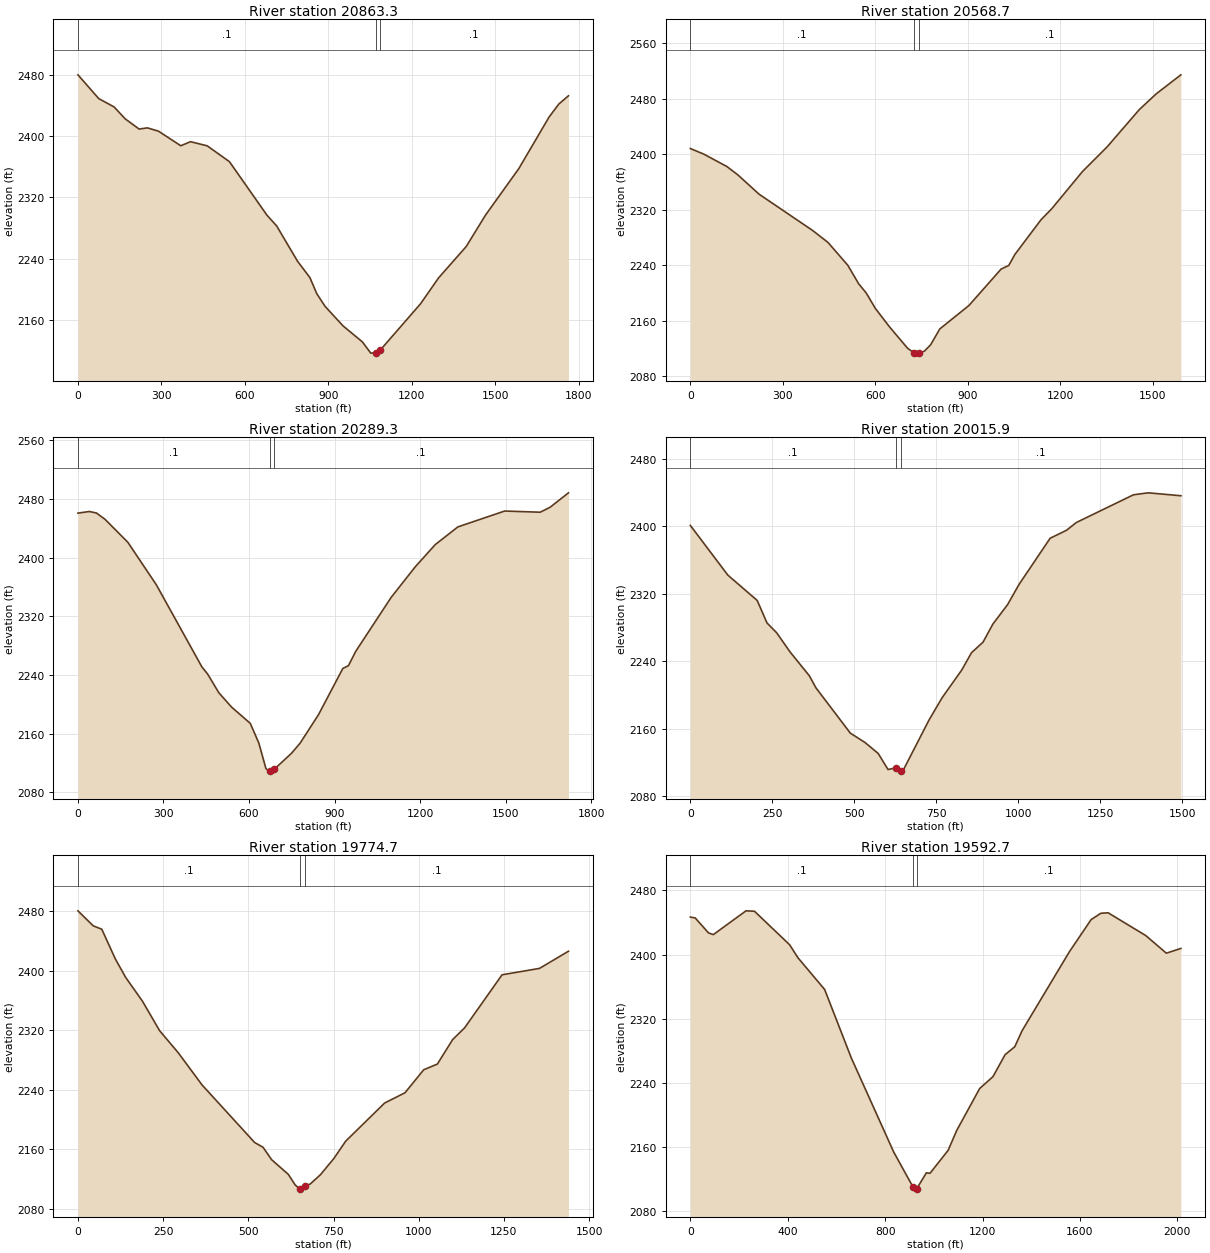
Type RM Length L Ch R = 1 ,20863.3 ,292.7,294.6,296.5
XS GIS Cut Line= 4
     1867021.058      174529.125     1867603.005      174952.359
     1868237.856      175315.131     1868487.262      175504.075
#Sta/Elev= 30
       0 2479.72      75 2448.67   129.9 2437.87   169.9 2422.32   219.9    2409
   249.8 2410.56   289.8 2406.19   369.8 2387.24   404.8 2392.52   464.7 2387.15
   544.7 2366.46   679.6  2296.7   714.6 2282.64   789.2 2236.85     834 2215.33
   858.8 2194.29   888.7 2177.74   953.4 2152.24    1023 2131.38  1052.8  2116.8
  1070.8 2117.38  1085.8 2120.27  1231.9 2181.17  1296.6 2214.89    1396 2255.82
  1465.7 2296.94  1584.9 2357.27  1694.1 2424.74  1728.9 2441.59  1763.7 2452.41
#Mann= 3 , 0 , 0
       0      .1       0  1070.8    .045       0  1085.8      .1       0
Bank Sta=1070.8,1085.8
XS Rating Curve= 0 ,0
Exp/Cntr=0.3,0.1

Type RM Length L Ch R = 1 ,20568.7 ,282.4,279.4,276.4
XS GIS Cut Line= 4
     1867172.213      175005.263     1867542.543      175216.881
     1868109.374      175594.768     1868577.955      175715.692
#Sta/Elev= 30
       0 2408.43    44.6 2400.13     119 2382.28   153.8 2370.51   223.2 2342.46
   396.8 2290.13   446.4 2272.96   511.1 2239.84   545.9 2213.37   570.7  2199.9
   600.6  2177.5   645.3 2151.56     705 2120.09   725.3 2113.76   740.3  2113.2
   744.8 2113.13   759.7 2116.08   779.6 2125.15   809.4 2148.05   903.9 2181.86
  1008.3 2234.41  1033.2 2239.67  1053.1 2255.57  1137.7 2305.53  1172.6 2321.48
  1272.4 2375.24  1352.2 2410.73    1457  2464.7  1511.9 2487.41  1591.7 2514.77
#Mann= 3 , 0 , 0
       0      .1       0   725.3    .045       0   740.3      .1       0
Bank Sta=725.3,740.3
XS Rating Curve= 0 ,0
Exp/Cntr=0.3,0.1

Type RM Length L Ch R = 1 ,20289.3 ,279.9,273.4,266.9
XS GIS Cut Line= 4
     1867041.747      175290.834     1867338.484      175466.286
     1868033.797      175806.385     1868623.302      175927.309
#Sta/Elev= 30
       0  2460.5      40 2462.75      65 2460.65    94.9 2452.14   174.9 2420.85
   274.8 2362.92   434.6 2250.99   454.6 2241.27   494.5 2215.46   539.5 2195.83
   604.4 2173.89   634.4 2147.14   659.3 2112.33   669.3 2108.74   672.7 2108.95
   687.7 2110.97   749.2 2133.14   779.2 2146.86   844.1 2185.93     929 2248.67
     949 2252.66   973.9 2271.81  1098.8 2345.75  1183.4 2387.47    1253 2417.54
  1332.6 2441.74  1496.7 2463.38  1621.1 2461.77  1655.9 2468.47  1720.5  2488.2
#Mann= 3 , 0 , 0
       0      .1       0   672.7    .045       0   687.7      .1       0
Bank Sta=672.7,687.7
XS Rating Curve= 0 ,0
Exp/Cntr=0.3,0.1

Type RM Length L Ch R = 1 ,20015.9 ,243.2,241.1,239.1
XS GIS Cut Line= 4
     1866960.596      175700.577     1867308.253      175821.501
     1867973.335      175934.867     1868419.242      176018.002
#Sta/Elev= 30
       0 2401.18   114.4 2342.25   203.9 2312.22   233.8 2285.54   263.6 2273.74
   303.4 2251.54   363.1 2222.79   383.1 2208.59     488 2154.87     533  2143.7
     573 2130.74     603  2111.7   626.3 2113.57   641.3  2110.1     643 2109.77
     648 2109.83   727.9 2170.24   767.9 2196.79   827.9 2229.72   857.8 2250.28
   892.8 2262.73   922.8 2284.15   967.8  2307.3  1002.8 2331.31  1097.6    2386
  1147.4 2395.42  1177.3 2404.61  1351.8 2437.55  1396.7 2439.86  1496.4 2436.42
#Mann= 3 , 0 , 0
       0      .1       0   626.3    .045       0   641.3      .1       0
Bank Sta=626.3,641.3
XS Rating Curve= 0 ,0
Exp/Cntr=0.3,0.1

Type RM Length L Ch R = 1 ,19774.7 ,182,182,182.1
XS GIS Cut Line= 4
     1866919.358      175958.733     1867354.166      176090.186
     1867753.582      176120.522     1868335.011      176181.193
#Sta/Elev= 30
       0 2480.03    44.9 2459.88    69.9 2455.41   109.8 2415.49   139.8 2390.96
   189.7 2358.55   239.6 2319.34   294.5 2289.61   364.4 2246.41   518.5 2169.33
   543.3 2162.87     568 2146.42   617.4 2126.56   637.2 2112.53   650.7 2107.03
     652 2106.79   665.7 2111.25   681.7  2113.7   711.4 2126.03     751 2147.89
   785.6 2171.09   899.8 2222.22   959.7 2236.05  1014.7  2266.9  1054.7 2274.51
  1099.6 2307.41  1134.6 2323.08  1244.5 2394.24  1354.5 2402.84  1439.4 2425.86
#Mann= 3 , 0 , 0
       0      .1       0   650.7    .045       0   665.7      .1       0
Bank Sta=650.7,665.7
XS Rating Curve= 0 ,0
Exp/Cntr=0.3,0.1

Type RM Length L Ch R = 1 ,19592.7 ,197.2,198.3,199.4
XS GIS Cut Line= 4
     1866643.171      176108.695     1867225.118       176259.85
     1868003.566      176320.312     1868615.744      176479.025
#Sta/Elev= 30
       0 2446.77    19.9 2445.74    74.5 2427.03    94.4  2424.9   228.6 2454.59
   263.4 2454.07   407.5 2412.31   442.2 2395.88   551.6  2356.4   660.9 2271.05
     835 2153.63   914.9 2109.64   924.5 2107.24   929.9  2107.9   969.3 2127.57
   984.2 2127.02  1058.8 2155.74  1093.6 2180.31  1188.1  2232.8  1242.8 2247.65
  1292.5 2275.03  1332.3 2284.96  1362.2 2304.85  1556.3 2403.37    1646 2443.67
  1685.8 2451.55  1715.7 2452.14  1870.1 2423.76  1954.7 2401.74  2014.5 2407.63
#Mann= 3 , 0 , 0
       0      .1       0   914.9    .045       0   929.9      .1       0
Bank Sta=914.9,929.9
XS Rating Curve= 0 ,0
Exp/Cntr=0.3,0.1