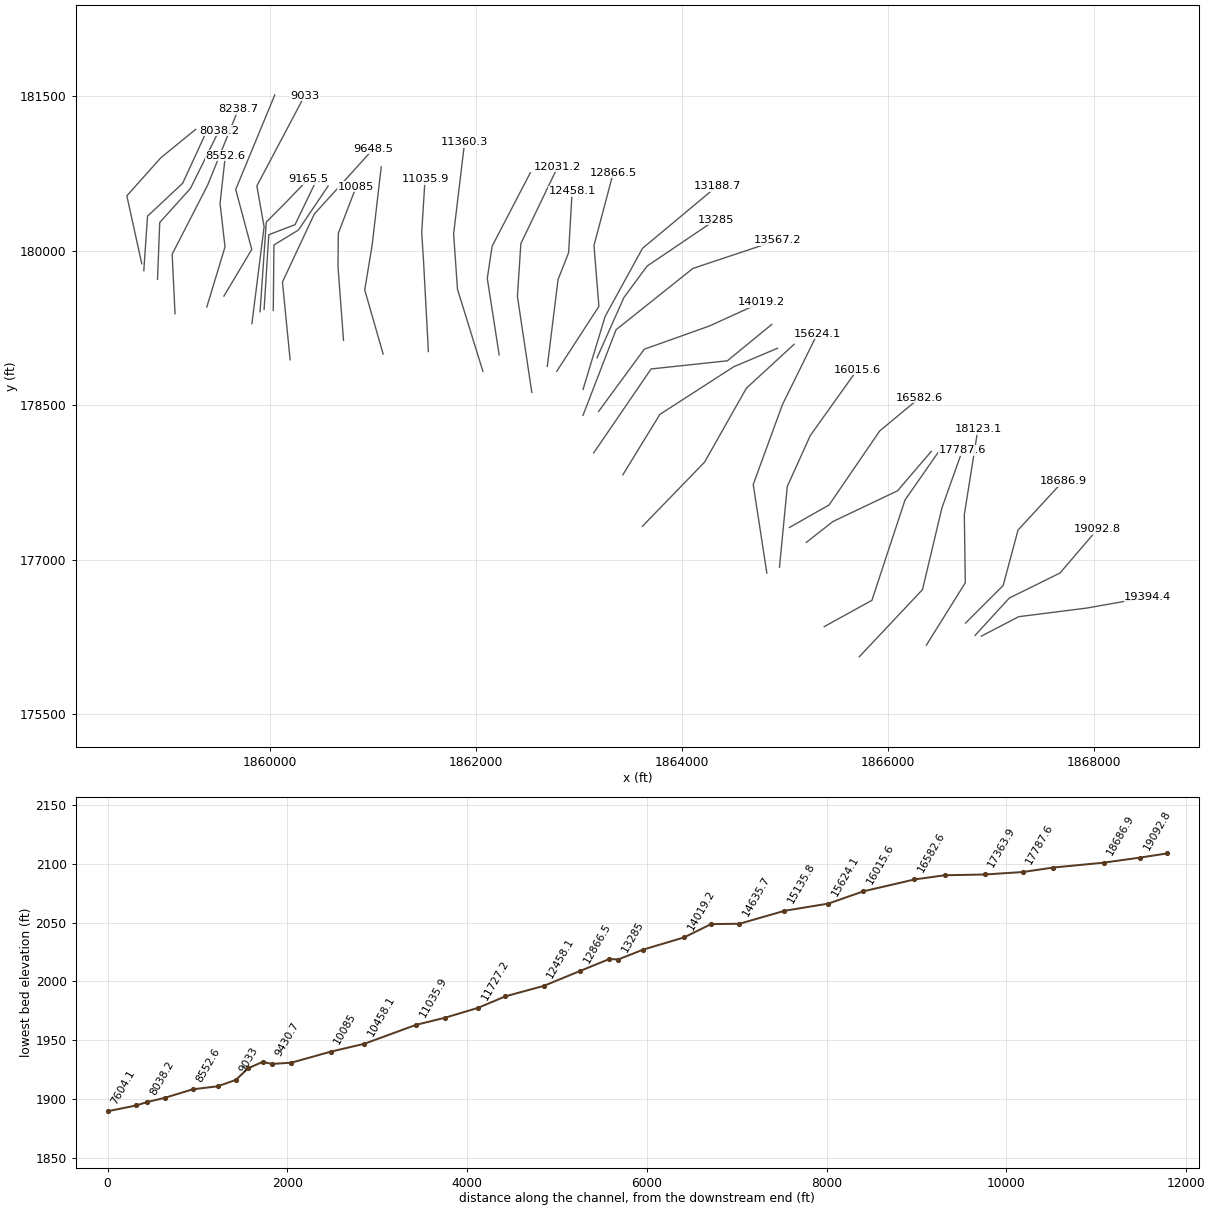
HEC-RAS study BeartownFk.prj: BeartownFk

--- BeartownFk.g01 (geometry) --- (continued)

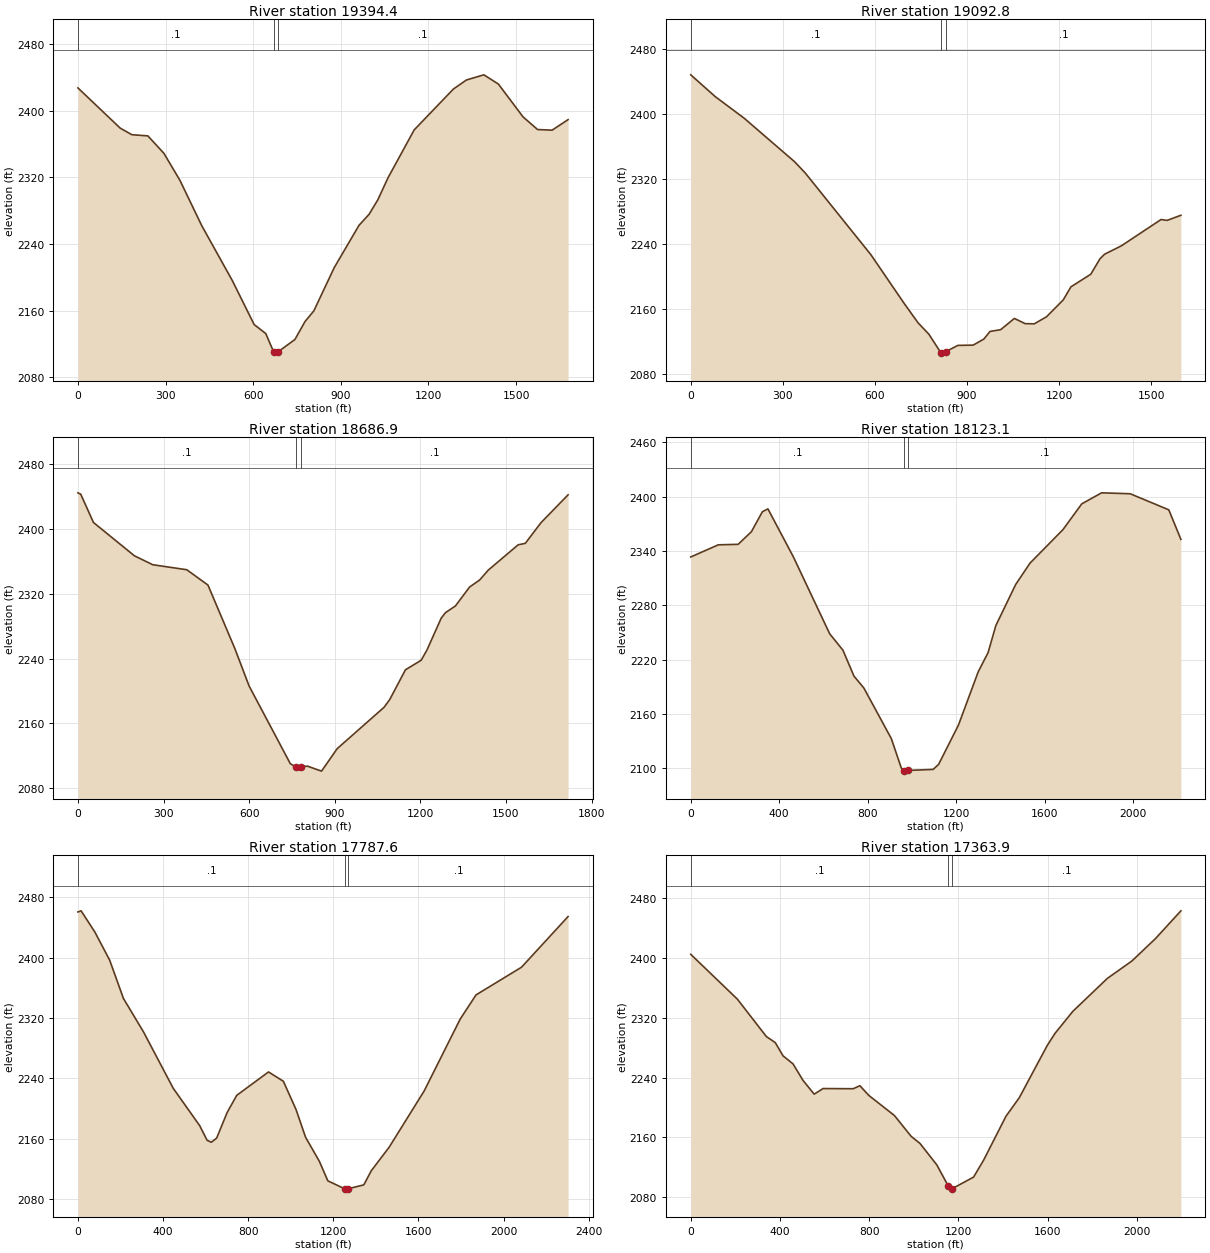
Type RM Length L Ch R = 1 ,19394.4 ,294,301.6,309.1
XS GIS Cut Line= 4
     1866907.692       176259.85     1867270.464      176448.794
     1867927.988      176531.929     1868525.051      176637.738
#Sta/Elev= 30
       0 2427.37   144.7  2379.1   184.6 2371.18   239.4 2369.78   294.3 2348.88
   349.2 2316.46     424 2261.96   528.6 2196.06   603.4 2143.23   643.2 2132.42
   669.9 2110.61   673.1 2108.93   684.9 2110.43   742.9 2125.28   777.8 2147.01
   807.7 2159.62   877.4 2211.47   962.2 2262.28     997 2275.67  1026.9 2293.05
  1061.8 2319.51  1151.3 2376.94  1285.5 2425.99  1330.2 2436.89  1389.9 2443.08
  1439.6 2431.98  1524.1 2392.56  1573.8 2377.39  1623.5 2376.62  1678.2 2389.28
#Mann= 3 , 0 , 0
       0      .1       0   669.9    .045       0   684.9      .1       0
Bank Sta=669.9,684.9
XS Rating Curve= 0 ,0
Exp/Cntr=0.3,0.1

Type RM Length L Ch R = 1 ,19092.8 ,386.7,405.9,425.1
XS GIS Cut Line= 4
     1866846.973      176267.267     1867179.514      176630.039
     1867670.768      176871.887      1868033.54      177295.121
#Sta/Elev= 30
       0 2448.04    79.5 2421.29     174 2394.64     338 2341.15   372.8  2327.3
   586.7  2226.7   696.2 2166.13     741 2142.54   775.9 2128.69   815.7 2105.37
   815.9 2105.37   830.9 2107.15   870.4  2114.9   920.2 2115.22   955.1  2122.7
     975 2132.07  1009.8 2134.24  1054.6 2148.09  1089.4  2141.7  1119.3 2141.42
  1159.1 2150.09  1213.9 2170.98  1238.8    2187  1303.5 2202.53  1333.3 2221.46
  1348.3 2227.13    1403 2237.48  1532.4 2269.87  1552.3 2268.81  1597.1 2275.11
#Mann= 3 , 0 , 0
       0      .1       0   815.9    .045       0   830.9      .1       0
Bank Sta=815.9,830.9
XS Rating Curve= 0 ,0
Exp/Cntr=0.3,0.1

Type RM Length L Ch R = 1 ,18686.9 ,558.9,563.8,565.1
XS GIS Cut Line= 4
      1866754.72      176387.225     1867119.309      176751.104
      1867264.14      177289.707     1867701.256      177763.843
#Sta/Elev= 30
       0 2444.86     9.9 2443.14    54.5 2408.21   198.1 2367.04   262.5 2356.01
   381.4 2349.85   455.7 2330.92     550 2252.43   599.8 2206.27   744.2  2110.3
   765.3 2105.75   780.3 2105.88   803.9 2107.26   853.7 2101.04   908.5 2128.77
  1072.8 2179.88  1092.8 2189.53  1147.8 2226.24  1202.8    2238  1222.8 2250.37
  1272.8 2289.81  1287.8 2296.77  1322.8 2305.06  1372.8 2328.57  1407.8 2337.15
  1437.8  2349.3  1542.8 2380.64  1567.8 2382.44  1622.7 2407.94  1717.7  2442.4
#Mann= 3 , 0 , 0
       0      .1       0   765.3    .045       0   780.3      .1       0
Bank Sta=765.3,780.3
XS Rating Curve= 0 ,0
Exp/Cntr=0.3,0.1

Type RM Length L Ch R = 1 ,18123.1 ,341.1,335.5,329.9
XS GIS Cut Line= 4
     1866373.926      176172.936     1866751.813      176777.556
     1866742.366       177438.86     1866874.627      178270.212
#Sta/Elev= 30
       0 2333.34   124.6 2346.75   214.4  2347.3   274.2 2361.23   324.1 2383.34
     349 2386.44   463.7 2333.59   628.2 2248.52   688.1 2230.42   737.9 2201.81
   782.6 2188.69   906.9 2132.77   951.7 2100.51   965.9 2097.04   971.6 2096.87
   980.9 2097.61  1095.9 2098.76  1120.8 2104.37  1210.3 2147.65  1299.8 2206.56
  1344.5 2227.78  1379.4 2257.58    1469 2302.89  1533.8 2326.49  1683.2 2363.61
  1767.9 2391.98  1857.5 2404.17    1987 2403.15  2161.4 2385.39  2216.2 2352.81
#Mann= 3 , 0 , 0
       0      .1       0   965.9    .045       0   980.9      .1       0
Bank Sta=965.9,980.9
XS Rating Curve= 0 ,0
Exp/Cntr=0.3,0.1

Type RM Length L Ch R = 1 ,17787.6 ,425.9,423.7,421.7
XS GIS Cut Line= 4
      1865722.07       176059.57     1866336.137      176711.426
     1866525.081       177504.99     1866723.472      178062.374
#Sta/Elev= 30
       0 2460.63    14.9 2462.16    79.6 2434.05   149.3 2396.67   213.9 2345.91
   308.5  2301.4   447.8  2226.8   572.2 2177.23     607 2157.79   626.9 2155.31
   651.8 2160.72   701.5 2194.91   746.3 2217.48   895.5 2248.49   965.2 2236.16
  1024.9 2198.57  1069.6 2161.88  1134.3 2130.01  1174.1 2104.13    1256 2093.16
  1258.6 2093.08    1271 2093.68  1343.2 2098.72    1378 2117.33  1462.6 2148.82
  1626.7 2223.25  1795.8 2318.45  1870.4 2350.64  2084.2  2387.4  2302.9 2454.57
#Mann= 3 , 0 , 0
       0      .1       0    1256    .045       0    1271      .1       0
Bank Sta=1256,1271
XS Rating Curve= 0 ,0
Exp/Cntr=0.3,0.1

Type RM Length L Ch R = 1 ,17363.9 ,462.2,443.6,425
XS GIS Cut Line= 4
     1865381.971      176352.433     1865844.883      176607.507
     1866166.088      177580.567     1866534.528       178109.61
#Sta/Elev= 30
       0 2404.78   209.4 2344.76   339.1 2294.86     379 2286.82   413.8 2269.11
   458.7 2258.34   503.6 2236.23   553.5 2217.91   593.5  2225.4   728.5 2225.16
   758.5 2229.19   798.5 2216.21   913.4 2189.35   988.4  2161.5  1028.4 2151.91
  1103.4  2123.4  1154.8 2095.08  1168.4 2090.99  1169.8 2091.18  1268.3 2107.09
  1313.3 2129.73  1413.3  2188.3  1473.3 2213.21  1598.2  2282.8  1633.2 2299.05
  1713.2 2328.54  1868.1  2372.6    1978 2395.81    2083 2425.52  2197.9  2462.9
#Mann= 3 , 0 , 0
       0      .1       0  1154.8    .045       0  1169.8      .1       0
Bank Sta=1154.8,1169.8
XS Rating Curve= 0 ,0
Exp/Cntr=0.3,0.1

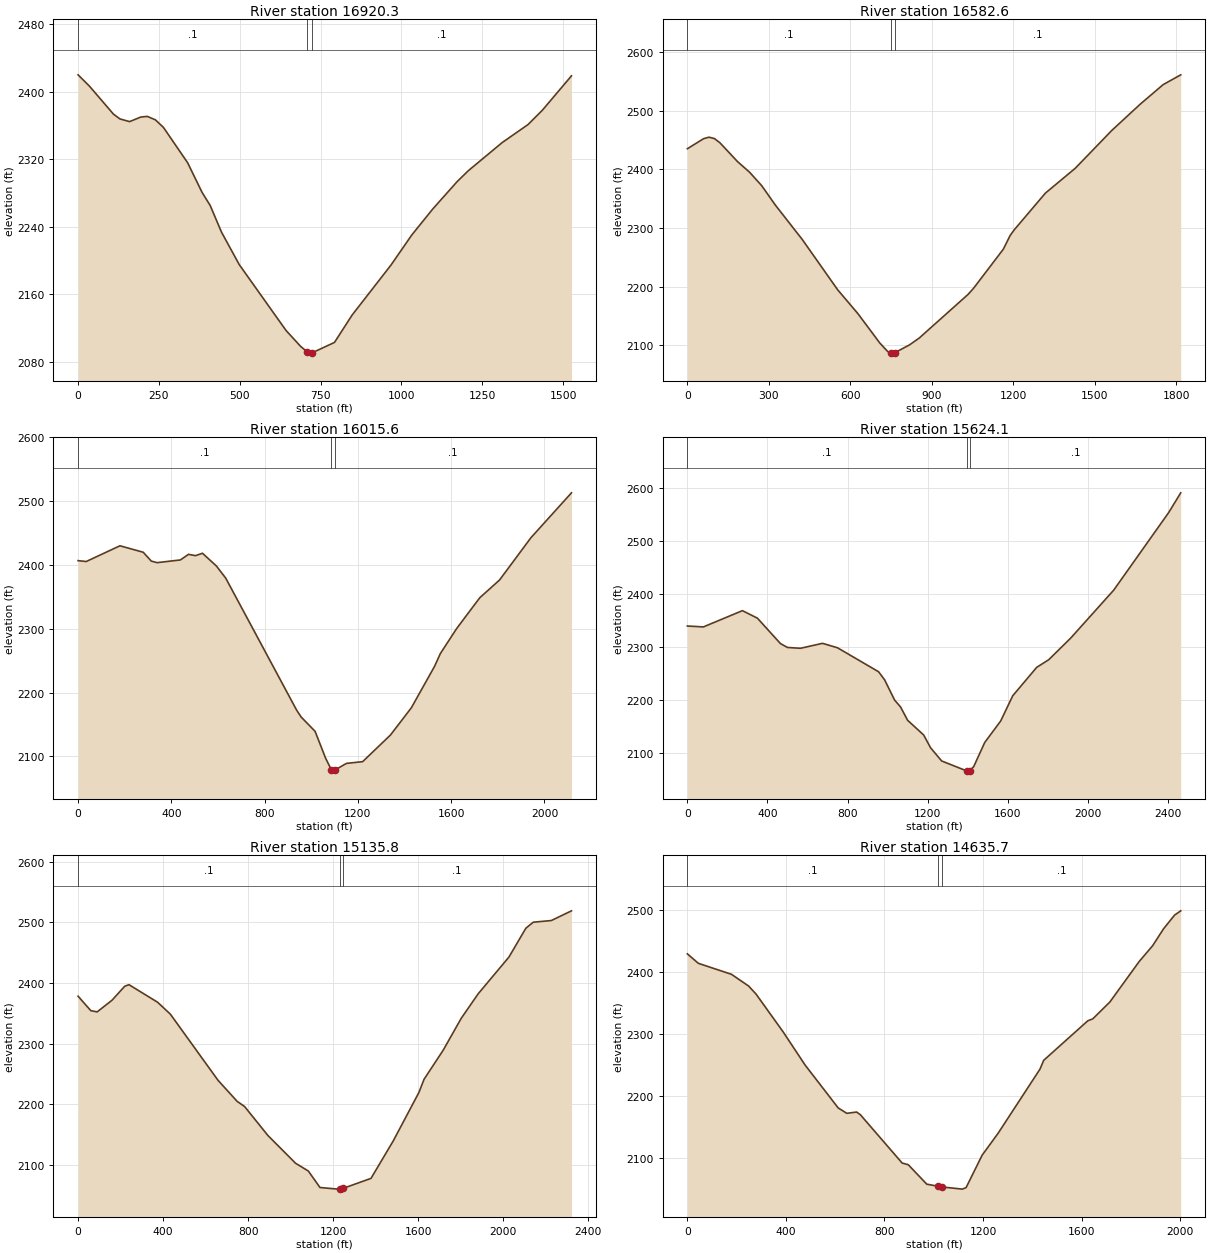
Type RM Length L Ch R = 1 ,16920.3 ,325.6,337.7,349.7
XS GIS Cut Line= 4
     1865208.117      177170.212     1865466.995      177372.729
     1866093.803      177670.481     1866421.162      178052.927
#Sta/Elev= 30
       0 2420.21    34.9 2406.88   109.6 2373.56   129.5 2367.94   159.4 2364.76
   194.2  2370.2   214.1 2370.92     239 2366.89   263.9 2357.94   338.7 2316.08
   383.6 2280.82   408.6 2265.36   443.5 2233.82   498.4 2195.31   643.2 2117.21
   688.1 2098.45   709.1 2091.64   718.1 2090.35   724.1 2090.76     793 2103.03
   847.9 2135.66   967.7 2194.69  1032.6 2230.64  1097.4 2261.37  1172.1 2293.51
    1207 2306.58  1311.7 2339.92  1391.4  2361.2  1436.3 2378.39    1526 2419.01
#Mann= 3 , 0 , 0
       0      .1       0   709.1    .045       0   724.1      .1       0
Bank Sta=709.1,724.1
XS Rating Curve= 0 ,0
Exp/Cntr=0.3,0.1

Type RM Length L Ch R = 1 ,16582.6 ,564.1,567,570.9
XS GIS Cut Line= 4
     1865043.751      177314.395     1865429.207      177533.331
     1865920.461      178251.318     1866307.795      178572.522
#Sta/Elev= 30
       0 2435.37    59.8 2452.47    79.7 2455.06    99.6 2452.68   119.5 2445.71
   184.3 2413.62   229.1  2395.3     274 2372.19   323.8 2339.37   423.4 2280.35
   553.3 2194.87   628.3 2153.87   708.3 2104.13   738.3 2089.17   748.3 2086.76
   750.1 2086.76   765.1 2087.75   818.3 2100.95   853.3 2112.35  1033.3 2186.84
  1053.3 2197.14  1163.3 2264.05  1188.3 2287.35  1203.3 2296.98  1318.2 2359.69
  1427.8  2401.9  1562.4 2466.45    1667 2511.26  1751.7 2544.72  1816.4  2561.4
#Mann= 3 , 0 , 0
       0      .1       0   750.1    .045       0   765.1      .1       0
Bank Sta=750.1,765.1
XS Rating Curve= 0 ,0
Exp/Cntr=0.3,0.1

Type RM Length L Ch R = 1 ,16015.6 ,390.1,391.4,393.8
XS GIS Cut Line= 4
       1864947.4      176928.711     1865022.978      177712.828
     1865246.374      178206.671     1865703.175      178846.491
#Sta/Elev= 30
       0  2406.8    34.9 2405.45   179.5 2430.12   279.2 2420.01   314.1 2406.05
     339 2403.68   438.8 2407.92   473.6 2416.71   503.6 2414.64   533.5 2418.39
   593.3 2398.39   633.2 2379.39   936.9 2172.56   956.8 2161.49  1016.5  2139.1
  1061.2 2097.27  1086.6 2078.38  1091.1  2076.7  1101.6 2078.44  1150.8 2088.82
  1220.4 2091.57  1339.7 2133.35  1429.3 2176.09  1528.8 2241.08  1553.7 2261.13
  1623.3 2300.23  1722.8 2348.69  1807.4 2376.41  1941.8 2442.69  2115.9 2513.18
#Mann= 3 , 0 , 0
       0      .1       0  1086.6    .045       0  1101.6      .1       0
Bank Sta=1086.6,1101.6
XS Rating Curve= 0 ,0
Exp/Cntr=0.3,0.1

Type RM Length L Ch R = 1 ,15624.1 ,490.4,488.3,485.1
XS GIS Cut Line= 4
     1864824.587      176872.028     1864692.326      177731.722
     1864975.742      178506.392      1865315.84      179196.037
#Sta/Elev= 30
       0 2339.88      80 2338.14   274.9 2368.84   349.9 2354.64   464.9 2306.73
   499.9 2299.42   564.9 2297.84   674.8 2307.21   749.8 2298.82   954.8 2253.63
   984.8 2238.46  1034.8 2200.29  1064.8 2187.09  1099.8 2162.13  1179.8 2134.44
  1214.8 2110.12  1269.8  2085.4  1395.3 2066.58  1399.7 2066.23  1410.3 2067.33
  1429.7 2074.63  1484.7 2120.16  1564.7 2160.86  1624.7 2208.34  1744.6 2261.98
  1804.5 2276.32  1914.4 2317.19  2129.1  2407.6  2403.7 2553.97  2463.6    2591
#Mann= 3 , 0 , 0
       0      .1       0  1395.3    .045       0  1410.3      .1       0
Bank Sta=1395.3,1410.3
XS Rating Curve= 0 ,0
Exp/Cntr=0.3,0.1

Type RM Length L Ch R = 1 ,15135.8 ,510.7,500.1,489.6
XS GIS Cut Line= 4
     1863615.346      177325.493     1864219.967      177949.008
     1864626.196      178666.994     1865089.108      179092.118
#Sta/Elev= 30
       0 2378.28    59.9 2354.45    89.8 2352.43   159.7 2371.67   219.6 2394.76
   239.6 2397.31   374.4 2368.29   434.3 2348.68   658.9 2239.46   748.7 2204.84
   783.7 2196.31   893.5 2148.49  1023.5 2102.77  1083.5    2090  1138.5 2062.72
  1223.5 2060.08  1231.7 2060.78  1246.7 2061.28  1378.5  2077.8  1483.5 2139.77
  1603.5 2219.18  1628.5 2241.44  1718.4 2289.31  1803.2 2341.86    1883 2382.31
  2027.7 2442.86  2107.5 2490.54  2142.4 2500.38  2227.2 2503.12    2322 2519.13
#Mann= 3 , 0 , 0
       0      .1       0  1231.7    .045       0  1246.7      .1       0
Bank Sta=1231.7,1246.7
XS Rating Curve= 0 ,0
Exp/Cntr=0.3,0.1

Type RM Length L Ch R = 1 ,14635.7 ,326.1,316,311
XS GIS Cut Line= 4
     1863426.403      177826.194     1863785.396       178411.92
     1864503.382      178874.832     1864928.506      179054.329
#Sta/Elev= 30
       0 2429.29    44.8 2413.98   179.2 2396.22   248.9 2377.21   278.8 2364.32
   388.3 2303.49   477.9 2249.65   612.3 2180.31   647.2 2171.59     687 2173.66
     702 2169.45   871.8 2091.27   896.8 2088.48   971.8 2057.09  1017.9 2053.73
  1032.9 2052.64  1116.6 2049.09  1131.6  2051.7  1196.6 2103.96  1261.5 2139.42
  1431.4 2243.04  1446.4 2257.22  1625.6 2321.17  1645.5  2324.2  1714.9 2351.41
    1834 2416.91  1888.6 2442.44  1933.3 2470.02  1977.9 2491.98  2002.7 2498.82
#Mann= 3 , 0 , 0
       0      .1       0  1017.9    .045       0  1032.9      .1       0
Bank Sta=1017.9,1032.9
XS Rating Curve= 0 ,0
Exp/Cntr=0.3,0.1

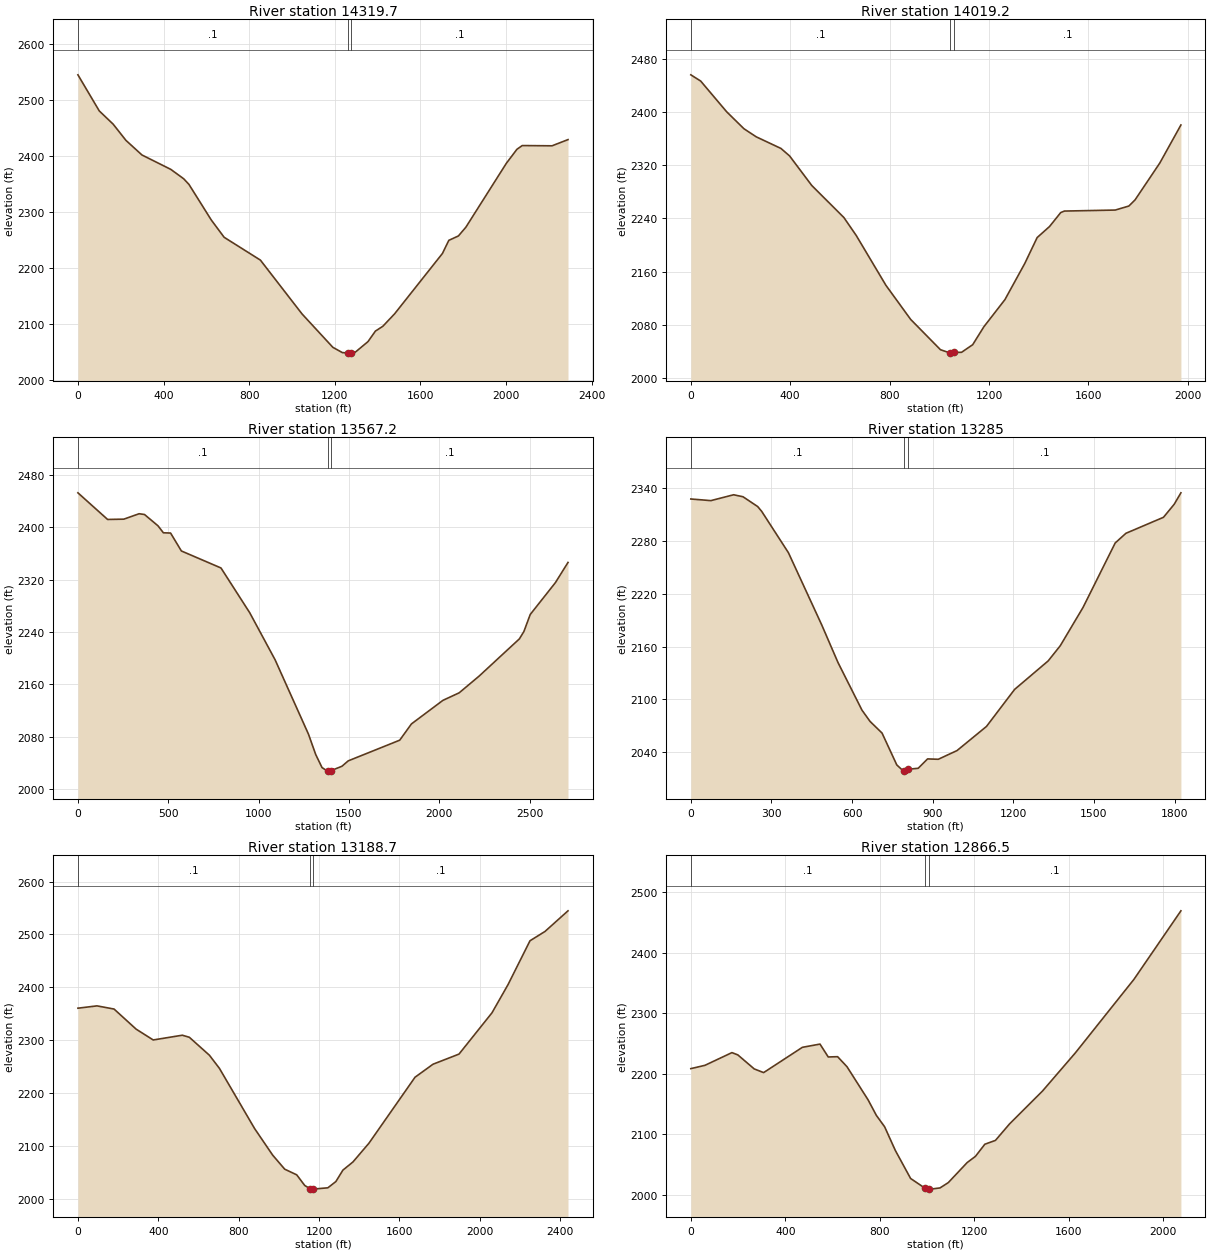
Type RM Length L Ch R = 1 ,14319.7 ,295,300.5,300.8
XS GIS Cut Line= 4
     1863142.987      178038.348     1863700.169       178853.22
     1864441.449      178932.386     1864871.823      179285.377
#Sta/Elev= 30
       0  2545.4    99.7 2481.01   164.5  2457.4   224.4 2428.42   299.1 2402.38
   433.8  2376.7   493.6 2360.08   518.5 2349.98   623.2 2286.24     683 2255.51
   852.5 2214.76  1046.8 2118.78  1190.9 2059.14  1235.6 2049.68    1262 2049.27
    1277 2049.38  1290.3  2048.8  1354.9  2069.3  1389.7 2088.12  1424.5 2096.76
  1479.2 2118.87  1702.8 2226.67  1732.6 2250.06  1777.4 2257.91  1812.2 2273.48
    2001 2387.34  2050.7 2412.53  2075.6 2419.18  2214.7 2418.73  2289.3  2429.8
#Mann= 3 , 0 , 0
       0      .1       0    1262    .045       0    1277      .1       0
Bank Sta=1262,1277
XS Rating Curve= 0 ,0
Exp/Cntr=0.3,0.1

Type RM Length L Ch R = 1 ,14019.2 ,445.2,452,458.5
XS GIS Cut Line= 4
     1863190.223      178440.262     1863634.241      179044.882
     1864268.724      179270.826     1864767.904      179498.347
#Sta/Elev= 30
       0 2455.78    39.7  2446.4   144.1 2400.29   213.6 2374.79   263.3 2362.57
   362.6 2345.15   397.4  2333.9   486.8 2289.42     616 2241.26   665.7 2214.27
   785.1 2139.41   884.8  2088.1  1004.6  2042.6  1044.3 2037.55  1049.5 2037.47
  1059.3 2038.55  1089.4 2038.69  1134.3 2050.13  1179.2 2077.06    1264 2117.89
  1343.8 2172.17  1393.7 2211.17  1443.6 2227.79  1488.5 2248.72  1503.4    2251
  1707.9 2252.51  1762.8 2258.57  1787.7 2267.82  1887.5 2323.35  1972.2 2380.39
#Mann= 3 , 0 , 0
       0      .1       0  1044.3    .045       0  1059.3      .1       0
Bank Sta=1044.3,1059.3
XS Rating Curve= 0 ,0
Exp/Cntr=0.3,0.1

Type RM Length L Ch R = 1 ,13567.2 ,276.5,282.2,288.1
XS GIS Cut Line= 4
     1863039.068      178402.473     1863360.272      179233.826
       1864106.6      179828.999     1864928.506      180102.967
#Sta/Elev= 30
       0 2452.85   164.3 2412.12   253.9 2412.57   338.6 2420.85   368.4 2419.72
   443.1 2402.42     473 2391.71   512.8 2391.33   572.6 2363.91   791.7 2337.91
   951.2 2269.27  1091.2 2197.49  1276.1 2083.62  1316.1 2052.51    1351 2032.61
    1381 2027.18  1384.5  2027.2  1399.5 2027.81    1461 2034.61    1496 2042.88
  1780.9 2074.51  1845.8  2099.4  2020.1 2135.44  2109.7 2146.91  2219.3 2172.28
  2443.3  2229.5  2468.2 2240.78  2503.1 2266.75  2642.5  2315.5  2712.2 2346.35
#Mann= 3 , 0 , 0
       0      .1       0  1384.5    .045       0  1399.5      .1       0
Bank Sta=1384.5,1399.5
XS Rating Curve= 0 ,0
Exp/Cntr=0.3,0.1

Type RM Length L Ch R = 1 ,13285   ,93.1,96.3,99.6
XS GIS Cut Line= 4
     1863175.484      178961.479     1863437.236      179547.576
     1863662.002      179852.006     1864327.763      180301.537
#Sta/Elev= 30
       0 2327.32    74.6 2325.46   159.2 2332.11   194.1 2329.87   248.8 2318.73
   263.7 2313.28   363.2 2266.39   487.6 2184.16   547.4 2141.98   636.9 2087.82
   666.8 2075.09   711.6 2061.82   766.4 2025.71   791.3 2018.67   792.8 2018.73
   807.8 2020.75     846  2021.9   880.9 2032.53   920.7  2032.1   990.4 2041.95
  1100.1 2069.34  1204.9 2111.38  1329.7 2143.67  1374.6 2160.84  1459.4 2204.31
  1579.1 2277.44    1619 2288.41  1758.8 2306.56  1798.7 2321.36  1823.6 2334.31
#Mann= 3 , 0 , 0
       0      .1       0   792.8    .045       0   807.8      .1       0
Bank Sta=792.8,807.8
XS Rating Curve= 0 ,0
Exp/Cntr=0.3,0.1

Type RM Length L Ch R = 1 ,13188.7 ,309.2,322.2,335.3
XS GIS Cut Line= 4
     1863039.699       178654.94     1863253.923      179362.809
     1863617.171      180024.108     1864343.669      180629.522
#Sta/Elev= 30
       0 2360.79      95 2365.19   179.9 2359.18   289.8 2321.25   374.8 2300.82
   519.7 2309.78   554.7 2305.88   654.6 2271.98   704.6 2247.14   879.5 2133.55
   969.4 2083.42  1029.4 2056.81  1089.3  2046.1  1129.3 2025.95  1157.6 2019.56
  1164.3 2019.12  1172.6 2019.24  1244.2  2021.6  1284.2 2033.43  1319.2 2054.99
  1369.2 2070.43  1449.1 2105.97  1678.2  2230.4  1767.8 2255.01  1897.2 2274.13
  2061.5 2352.16  2141.1 2405.25  2250.6 2488.11  2325.3 2505.74  2439.8 2544.68
#Mann= 3 , 0 , 0
       0      .1       0  1157.6    .045       0  1172.6      .1       0
Bank Sta=1157.6,1172.6
XS Rating Curve= 0 ,0
Exp/Cntr=0.3,0.1

Type RM Length L Ch R = 1 ,12866.5 ,418.5,408.3,398
XS GIS Cut Line= 4
      1862784.11      178830.458     1863193.493      179460.145
     1863145.862      180052.422      1863333.64       180758.47
#Sta/Elev= 30
       0 2208.47    59.7 2213.92   174.1 2234.96     199 2231.22   268.6 2207.97
   308.4 2201.89   472.5 2243.73   547.1 2249.08     582 2227.76   621.7 2228.24
   661.5 2211.63   751.1 2156.61     786 2131.01     821 2112.19   865.9 2073.32
   930.8 2026.75   993.3  2010.2  1008.3 2009.27  1015.7 2009.07  1055.6 2011.07
  1090.6 2019.86  1170.5 2053.03  1205.4 2063.25  1245.4 2083.38  1290.3 2089.72
  1350.2 2117.08  1489.4 2171.33  1628.6 2234.48    1877 2356.28  2075.8  2469.6
#Mann= 3 , 0 , 0
       0      .1       0   993.3    .045       0  1008.3      .1       0
Bank Sta=993.3,1008.3
XS Rating Curve= 0 ,0
Exp/Cntr=0.3,0.1

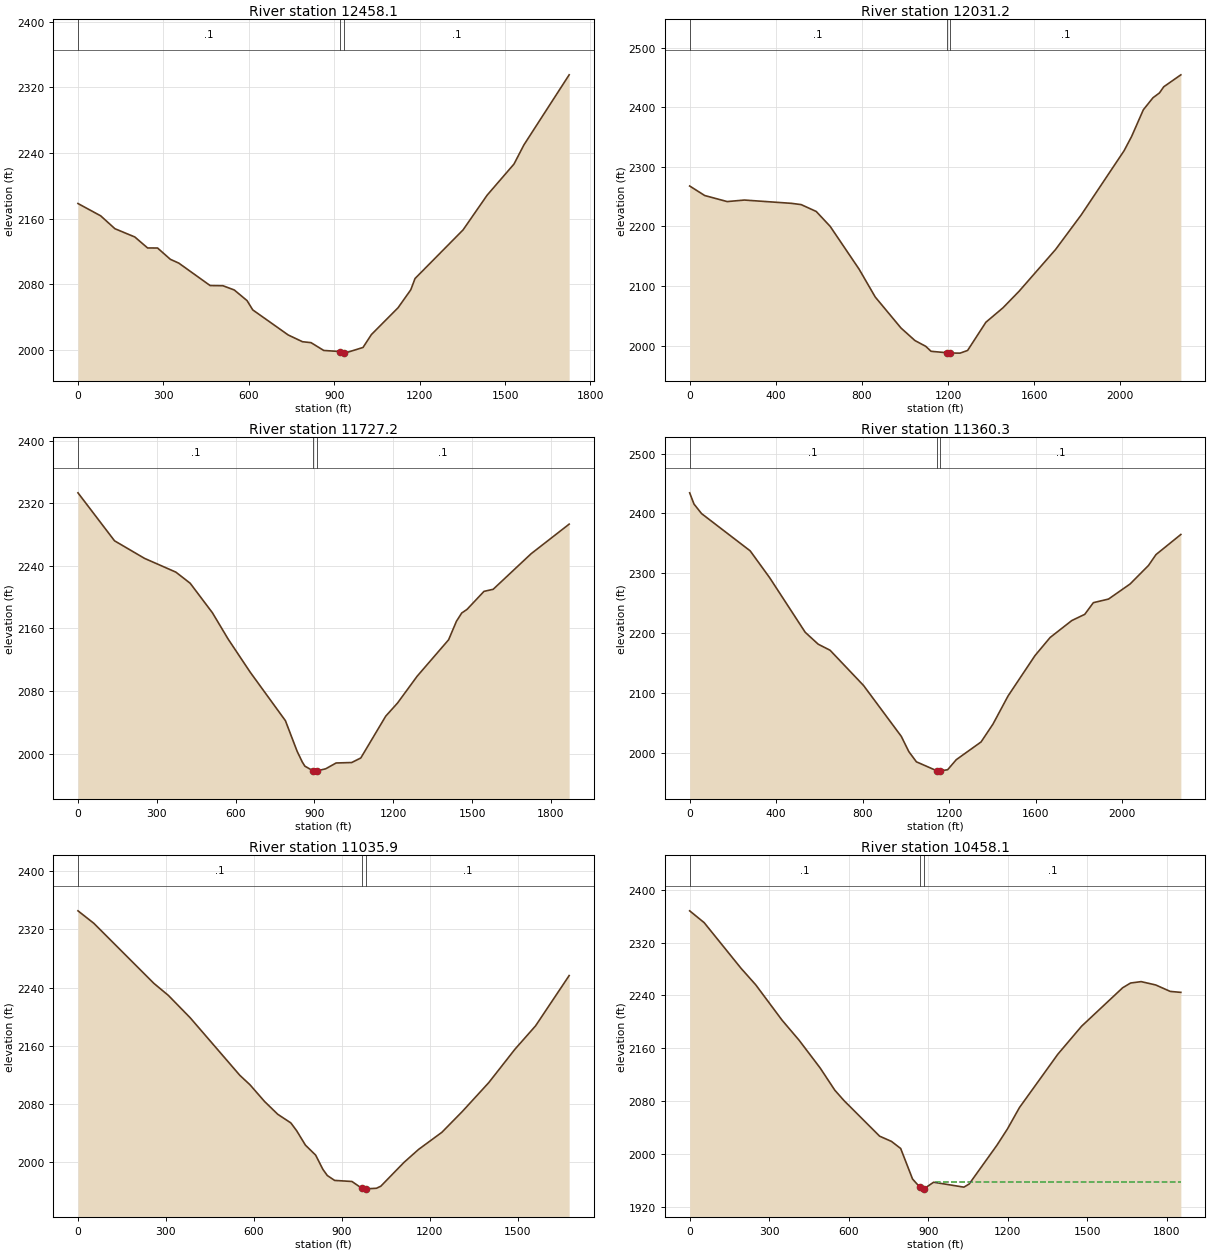
Type RM Length L Ch R = 1 ,12458.1 ,419.8,426.9,434.1
XS GIS Cut Line= 4
     1862692.603      178878.595     1862796.958      179720.632
     1862899.425      179982.011     1862933.699      180577.063
#Sta/Elev= 30
       0 2178.57    79.9 2163.53   129.8 2147.86   199.6 2137.81   244.6  2124.4
   279.5 2124.35   324.4 2110.59   354.4 2105.88   464.2  2078.6   509.1 2078.38
     549  2073.2   593.9 2060.24   613.9 2048.93   738.7 2018.31   788.6 2010.14
   818.5 2009.03   863.3  1999.5   920.1 1998.17   935.1 1996.45   937.1 1996.24
  1001.2 2003.13  1030.7 2018.88  1124.3 2051.54    1169 2073.44  1183.9 2087.15
  1352.7 2146.43  1437.2 2188.74  1531.6 2226.71  1566.3 2249.96  1725.3 2335.41
#Mann= 3 , 0 , 0
       0      .1       0   920.1    .045       0   935.1      .1       0
Bank Sta=920.1,935.1
XS Rating Curve= 0 ,0
Exp/Cntr=0.3,0.1

Type RM Length L Ch R = 1 ,12031.2 ,306.1,304,301.9
XS GIS Cut Line= 4
     1862541.944      178625.548     1862402.233      179556.955
     1862435.538      180069.997     1862793.424      180814.354
#Sta/Elev= 30
       0 2267.87    69.8  2251.9   174.4 2241.71   254.1 2244.29   473.4 2238.75
   518.2 2236.63     588 2225.11   652.8 2200.07   787.4 2128.13   862.1 2081.53
   981.8 2029.47  1046.6 2008.44  1096.6  1998.8  1121.5 1990.41    1194    1988
    1209  1987.5  1256.3 1987.34  1291.2 1991.84  1376.1 2039.16    1456 2063.57
  1530.6  2091.3  1699.8 2161.25  1819.2 2219.43  2018.2 2327.11    2053 2350.95
  2107.7 2395.87  2152.5 2416.03  2182.4 2424.05  2202.3 2434.38  2281.9 2454.48
#Mann= 3 , 0 , 0
       0      .1       0    1194    .045       0    1209      .1       0
Bank Sta=1194,1209
XS Rating Curve= 0 ,0
Exp/Cntr=0.3,0.1

Type RM Length L Ch R = 1 ,11727.2 ,362.1,366.9,367.8
XS GIS Cut Line= 4
     1862224.805      178990.147     1862109.654      179731.427
     1862156.434      180044.492     1862527.074      180756.985
#Sta/Elev= 30
       0 2333.52   139.1 2272.17   253.4 2249.67   372.6  2232.1   427.2 2217.85
   511.7 2180.16   571.3 2146.66   655.8 2104.03   789.7 2042.08   834.2 2002.99
     854 1989.18   863.9 1983.87   894.1 1978.15   903.5 1977.56   909.1  1977.8
   943.1 1980.56   982.6 1987.97    1042 1988.56  1076.7  1994.4  1171.5 2047.84
  1216.4 2064.62  1291.2 2098.98  1410.9 2145.56  1440.8  2169.3  1460.8  2179.8
  1480.8 2184.36  1545.6 2207.48  1580.5 2210.13  1725.2 2255.68  1869.8 2293.46
#Mann= 3 , 0 , 0
       0      .1       0   894.1    .045       0   909.1      .1       0
Bank Sta=894.1,909.1
XS Rating Curve= 0 ,0
Exp/Cntr=0.3,0.1

Type RM Length L Ch R = 1 ,11360.3 ,324.7,324.4,327.9
XS GIS Cut Line= 4
     1862066.926      178830.458     1861820.154      179627.089
     1861782.557      180164.196     1861889.959       181056.52
#Sta/Elev= 30
       0 2434.41      20 2415.66    54.9 2399.72   279.7 2337.45   369.6 2292.66
   534.3 2201.26   594.3 2181.36   649.2 2171.27     804 2112.35   978.6 2027.27
  1013.4  2001.8  1048.4 1984.73    1142  1969.9    1153 1969.18    1157 1969.46
  1192.9 1971.53  1232.8 1988.34  1347.5 2017.98  1402.4 2047.76  1472.3 2094.89
  1597.1  2162.5    1667 2192.68  1766.9 2220.88  1826.8 2231.27  1866.7  2250.8
  1936.6 2256.79  2036.5 2282.02  2121.4 2312.92  2156.3 2331.19  2271.2 2364.78
#Mann= 3 , 0 , 0
       0      .1       0    1142    .045       0    1157      .1       0
Bank Sta=1142,1157
XS Rating Curve= 0 ,0
Exp/Cntr=0.3,0.1

Type RM Length L Ch R = 1 ,11035.9 ,583.5,577.8,572.1
XS GIS Cut Line= 4
     1861537.501      179022.533     1861490.721      179896.956
     1861472.729      180177.635     1861505.115      180695.812
#Sta/Elev= 30
       0 2345.42    54.7 2328.09   258.7 2245.88   308.5  2229.2   383.1 2198.43
   552.3 2119.45   587.1 2106.39   636.8 2083.44   681.6 2065.94   726.4 2054.03
   746.3 2043.26   776.2 2023.49     811 2009.81   835.9 1990.12   850.8 1981.78
   875.7 1975.05   934.9 1973.56   968.7 1964.24   979.3 1963.07   983.7 1963.44
  1018.8 1964.28  1033.6 1967.16  1112.5  1999.8  1161.9  2017.5  1241.8 2041.14
  1311.7  2069.8  1401.6 2109.32  1491.4 2155.42  1561.3  2187.3  1676.1 2256.47
#Mann= 3 , 0 , 0
       0      .1       0   968.7    .045       0   983.7      .1       0
Bank Sta=968.7,983.7
XS Rating Curve= 0 ,0
Exp/Cntr=0.3,0.1

Type RM Length L Ch R = 1 ,10458.1 ,369.6,373.1,376.6
XS GIS Cut Line= 4
     1861098.263      178998.111     1860919.376      179619.684
     1860991.505      180055.896     1861079.635      180814.354
#Sta/Elev= 30
       0 2368.11    54.7 2350.22     194    2281   248.8 2256.32   348.3 2202.69
     413 2172.12   492.6 2129.99   547.3  2096.7   582.1  2080.9   716.4 2027.05
   761.1 2019.13   795.8 2008.42   840.6 1962.18   868.5 1949.78   880.3  1946.9
   883.5 1947.33     920 1957.35  1034.3 1949.89  1054.2 1954.68  1158.8 2013.34
  1198.7 2038.13  1243.6 2070.24  1388.4 2151.03  1478.2  2193.5  1632.9 2251.62
  1662.9 2258.84  1702.8 2260.96  1757.7  2255.9  1812.6 2246.13  1852.5 2244.69
#Mann= 3 , 0 , 0
       0      .1       0   868.5    .045       0   883.5      .1       0
#XS Ineff= 2 , 0
                          923.53         1957.17
Permanent Ineff=
       F       F
Bank Sta=868.5,883.5
XS Rating Curve= 0 ,0
Exp/Cntr=0.3,0.1

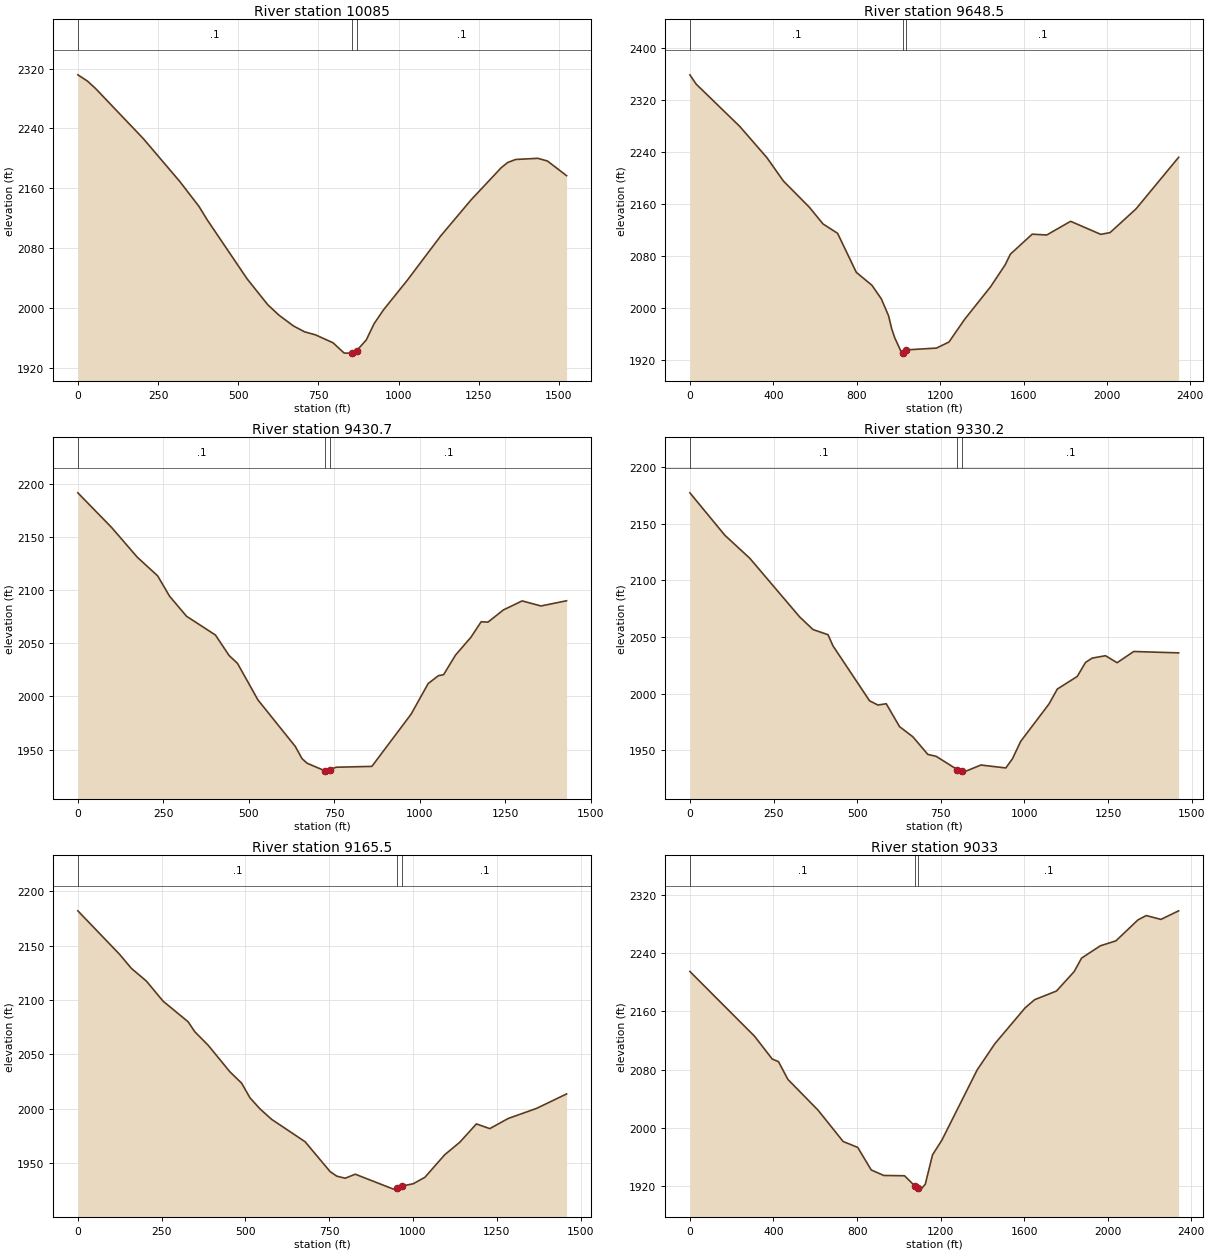
Type RM Length L Ch R = 1 ,10085   ,446.1,436.5,426.8
XS GIS Cut Line= 4
     1860713.456      179130.486     1860659.479      179850.176
     1860663.078      180170.438     1860835.803      180620.244
#Sta/Elev= 30
       0 2311.62    29.9 2303.31    54.8 2293.56   204.1  2226.5   318.6 2168.88
   378.3 2135.64   403.2  2118.2   527.6 2039.45   592.3 2004.75   627.1  1990.9
   671.9 1976.59   706.8  1968.7   741.4 1964.55   795.6 1954.04   830.1 1940.41
     835 1940.23   854.4 1940.25   869.4 1943.55   899.1  1957.7   923.7 1979.52
   953.3 1998.16  1027.2 2037.48  1131.4 2096.66  1225.8 2144.63  1320.2 2187.76
    1340 2194.56  1364.9 2198.66  1434.4 2200.19  1464.2 2196.59  1523.8 2177.02
#Mann= 3 , 0 , 0
       0      .1       0   854.4    .045       0   869.4      .1       0
Bank Sta=854.4,869.4
XS Rating Curve= 0 ,0
Exp/Cntr=0.3,0.1

Type RM Length L Ch R = 1 ,9648.5  ,231,217.8,204.7
XS GIS Cut Line= 4
     1860194.799      178942.227     1860120.286      179696.666
      1860429.64      180356.748     1861005.123      180991.321
#Sta/Elev= 30
       0 2358.72    29.9 2344.52   239.4 2279.31   369.1 2231.48   448.9 2195.29
   573.6 2154.94   638.4 2129.46   708.2  2115.1     798 2055.11     873 2035.19
   917.9 2014.36   952.8  1988.3   967.8 1968.24   982.8 1954.12  1012.8 1933.24
  1022.2 1930.88  1037.2 1935.86  1182.5 1938.63  1242.4 1947.97  1317.3 1982.74
  1442.2 2033.03    1512 2066.69  1536.9 2083.01  1641.5 2113.76  1711.2 2112.48
  1825.8 2133.53  1970.2  2113.5    2015 2116.19  2139.5 2152.64  2343.8 2231.94
#Mann= 3 , 0 , 0
       0      .1       0  1022.2    .045       0  1037.2      .1       0
Bank Sta=1022.2,1037.2
XS Rating Curve= 0 ,0
Exp/Cntr=0.3,0.1

Type RM Length L Ch R = 1 ,9430.7  ,104.7,100.4,96.7
XS GIS Cut Line= 4
     1860031.231      179420.798     1860037.443      180056.563
     1860275.597      180201.526     1860563.452      180628.131
#Sta/Elev= 30
       0  2191.3    99.3 2158.56   173.8 2130.83   233.5 2113.27   268.2 2094.19
   317.9 2075.34   402.3 2057.75   442.1 2038.56   466.9 2031.08   526.5 1996.82
   635.8 1953.08   655.7 1941.54   670.6 1937.26   722.3 1930.16   725.4 1929.86
   737.3 1931.26   755.3 1933.52   859.8 1934.31   974.6  1983.4  1024.5 2012.13
  1054.5 2019.56  1069.5 2020.43  1104.5 2038.91  1149.4 2055.58  1179.4 2070.18
  1199.4 2069.83  1244.4 2081.28  1299.3 2089.78  1354.3 2085.02  1429.2  2089.9
#Mann= 3 , 0 , 0
       0      .1       0   722.3    .045       0   737.3      .1       0
Bank Sta=722.3,737.3
XS Rating Curve= 0 ,0
Exp/Cntr=0.3,0.1

Type RM Length L Ch R = 1 ,9330.2  ,155,164.7,173.7
XS GIS Cut Line= 4
     1859942.182      179431.152     1859987.742      180155.967
     1860242.462      180253.299      1860443.34      180669.549
#Sta/Elev= 30
       0 2177.24   104.5 2139.79   179.1 2119.46   328.3 2067.65   368.1 2056.56
   412.9 2052.01   427.8 2042.11   537.2 1993.64   562.1 1989.93     587 1991.05
   626.8 1970.84   666.6 1961.88   711.3 1946.35   736.2 1944.65   799.9 1932.84
   814.9 1931.83   825.4 1931.58     870 1936.97   944.4 1934.38   964.2 1942.47
     989 1957.88  1073.5 1990.83  1098.3 2003.98    1158 2015.18  1182.8 2027.53
  1202.7 2031.34  1242.4 2033.46  1277.2 2027.28  1326.9 2037.18  1461.1 2035.97
#Mann= 3 , 0 , 0
       0      .1       0   799.9    .045       0   814.9      .1       0
Bank Sta=799.9,814.9
XS Rating Curve= 0 ,0
Exp/Cntr=0.3,0.1

Type RM Length L Ch R = 1 ,9165.5  ,111.6,132.5,153.7
XS GIS Cut Line= 4
     1859902.924      179408.383     1859963.163      180278.836
     1860137.856      180453.529     1860372.788      180697.497
#Sta/Elev= 30
       0 2181.94   124.6 2141.93   159.6 2129.06   204.4  2117.4   254.3  2098.9
   329.1 2079.92     349 2070.75   388.9 2058.35   453.7 2033.94   488.6 2023.51
   513.6 2010.06   543.5 1999.82   578.4 1990.18   678.1 1969.64   752.9 1942.12
   772.8 1937.97   797.8 1936.08   827.7 1939.79   941.7 1926.06     953 1927.01
     968 1928.89    1001 1931.03  1035.6 1936.94  1094.9 1957.74  1139.5 1969.11
  1189.3 1986.03  1229.2  1981.7    1284 1990.99  1368.6 2000.28  1458.3 2013.57
#Mann= 3 , 0 , 0
       0      .1       0     953    .045       0     968      .1       0
Bank Sta=953,968
XS Rating Curve= 0 ,0
Exp/Cntr=0.3,0.1

Type RM Length L Ch R = 1 ,9033    ,201.3,204.8,208.6
XS GIS Cut Line= 4
     1859823.693      179293.384      1859942.08      180233.657
      1859871.78      180629.498      1860334.51      181503.595
#Sta/Elev= 30
       0 2214.48   309.2  2125.9     394 2094.56     424 2090.97   468.9 2066.66
   613.5 2024.45   733.2 1981.62     803 1973.48   867.9 1942.54   927.8 1935.03
  1027.1 1934.63  1078.6 1920.04  1093.6 1917.47  1106.5 1916.31  1126.4 1923.05
  1161.1 1963.28  1205.8  1983.4  1374.7 2079.67  1459.6 2115.67  1604.5 2164.79
  1649.4 2175.82  1754.3 2187.79  1839.2 2214.48  1874.2 2232.83  1964.1 2249.71
    2039 2256.57    2144 2285.18  2183.9 2291.19  2253.8 2285.88  2338.8 2297.65
#Mann= 3 , 0 , 0
       0      .1       0  1078.6    .045       0  1093.6      .1       0
Bank Sta=1078.6,1093.6
XS Rating Curve= 0 ,0
Exp/Cntr=0.3,0.1

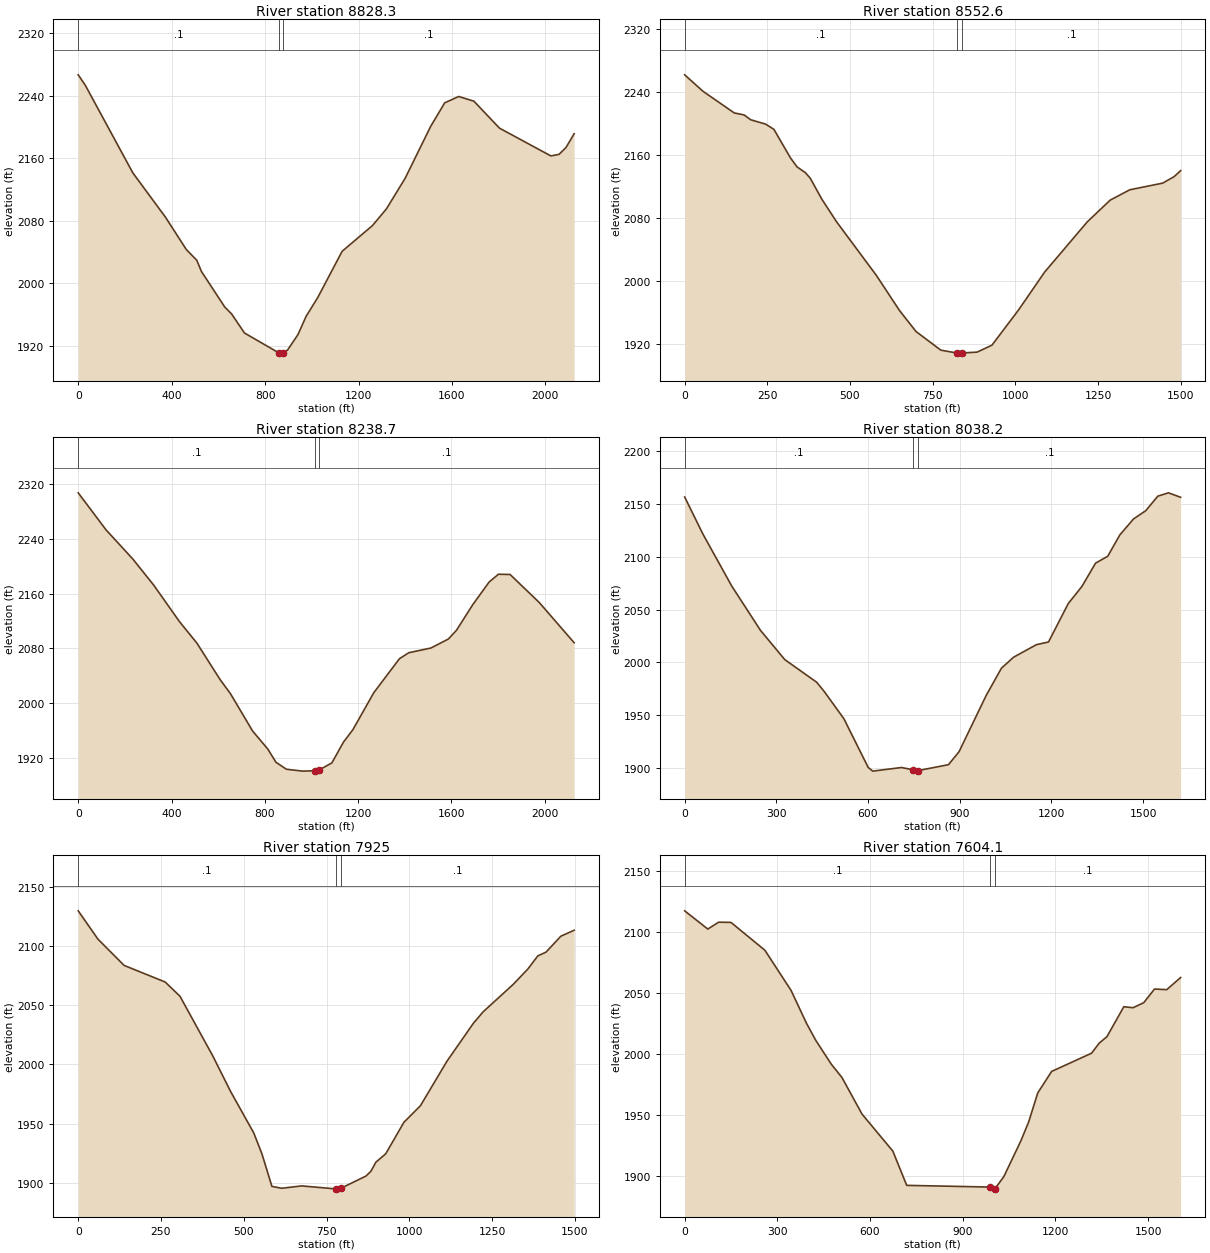
Type RM Length L Ch R = 1 ,8828.3  ,280.1,275.7,270.1
XS GIS Cut Line= 4
     1859551.923      179560.296     1859822.236      180013.344
     1859666.307      180595.055     1860045.774      181512.909
#Sta/Elev= 30
       0 2266.92    29.9 2253.82   233.9 2141.44   373.3 2084.88   462.9 2043.35
   507.6  2029.6   527.6 2015.27   627.1 1969.92     657 1960.82   711.7 1936.58
   860.1 1910.93     866 1910.81   875.1 1911.55   895.9  1914.6   940.7 1934.52
   975.5 1957.84  1025.3 1981.89  1129.8 2041.12  1259.6 2074.01  1319.5 2095.43
  1399.3  2134.4  1509.1  2201.1    1569 2231.12  1628.9 2239.19  1693.8  2233.2
  1803.6 2198.64  2023.2 2163.17  2058.1 2165.13  2088.1 2173.89    2123 2191.59
#Mann= 3 , 0 , 0
       0      .1       0   860.1    .045       0   875.1      .1       0
Bank Sta=860.1,875.1
XS Rating Curve= 0 ,0
Exp/Cntr=0.3,0.1

Type RM Length L Ch R = 1 ,8552.6  ,329.5,313.9,297.2
XS GIS Cut Line= 4
     1859385.628      179454.347     1859562.574       180037.88
     1859514.383      180459.553     1859565.551      180922.514
#Sta/Elev= 30
       0 2261.64      55 2240.86   149.9 2213.28   179.9 2210.66   199.9 2204.55
   244.9 2199.04   269.9 2192.41   319.9 2156.22   339.9 2144.71   364.9 2137.49
   379.9 2130.28   414.8 2103.79   459.8 2074.81   579.8 2006.95   649.7 1962.43
   699.6 1935.75   774.6 1912.07   824.1 1908.32   829.5 1908.26   839.1 1908.45
   884.4 1909.54   929.3 1918.32  1009.2  1962.7  1088.7 2011.16  1217.5 2074.87
  1286.9  2102.5  1346.4 2115.69  1445.5 2124.09  1480.2 2132.32    1500 2139.98
#Mann= 3 , 0 , 0
       0      .1       0   824.1    .045       0   839.1      .1       0
Bank Sta=824.1,839.1
XS Rating Curve= 0 ,0
Exp/Cntr=0.3,0.1

Type RM Length L Ch R = 1 ,8238.7  ,207,200.5,194
XS GIS Cut Line= 4
     1859077.111      179389.302     1859049.168      179966.774
     1859393.789      180637.387     1859691.839      181373.198
#Sta/Elev= 30
       0 2307.11   119.6 2252.95   234.2 2210.47     324 2172.26   433.6 2119.37
   508.4 2087.98   608.1 2034.67     653 2013.78   747.9 1959.37   812.8 1933.18
   847.8 1913.85   892.7 1903.71   962.6 1900.96  1015.5 1901.57  1030.5 1902.16
  1087.5 1913.03  1137.4 1943.44  1177.3 1961.35  1267.2 2015.45  1377.1 2065.04
    1417 2073.74  1511.9 2080.62  1586.8 2093.74  1621.7 2106.57  1691.6    2144
  1761.5  2176.9  1801.5 2188.32  1851.4  2187.9  1976.2 2147.15    2126 2088.32
#Mann= 3 , 0 , 0
       0      .1       0  1015.5    .045       0  1030.5      .1       0
Bank Sta=1015.5,1030.5
XS Rating Curve= 0 ,0
Exp/Cntr=0.3,0.1

Type RM Length L Ch R = 1 ,8038.2  ,114.4,113.2,112
XS GIS Cut Line= 4
     1858907.035       179724.23     1858928.625      180274.793
     1859227.297       180605.85     1859504.377      181167.208
#Sta/Elev= 30
       0 2156.31    59.6 2121.35   153.9 2072.24   248.2 2030.26   327.6 2002.67
   431.8 1981.34   456.7 1972.56   521.2 1946.74   600.5 1900.82   615.4 1897.31
   709.5 1900.73   748.2  1898.5   763.2 1897.81   863.1 1903.39   897.8 1915.64
     987    1969  1036.6 1994.57  1076.4 2004.96  1150.9 2016.78  1190.6 2019.33
  1255.2 2055.61  1299.9 2071.82  1344.6 2093.83  1384.4 2100.32  1424.1 2120.52
  1468.9 2135.61  1508.6 2143.32  1548.4 2157.12  1583.1 2160.26  1622.9 2156.05
#Mann= 3 , 0 , 0
       0      .1       0   748.2    .045       0   763.2      .1       0
Bank Sta=748.2,763.2
XS Rating Curve= 0 ,0
Exp/Cntr=0.3,0.1

Type RM Length L Ch R = 1 ,7925    ,318.8,320.8,322.8
XS GIS Cut Line= 4
     1858773.892      179806.995     1858809.876      180335.967
     1859151.729      180656.229     1859360.439      181109.633
#Sta/Elev= 30
       0 2129.88    59.5 2105.97   138.7  2083.7   262.6 2069.69   307.2  2057.7
   406.3 2007.25   460.8  1976.8   530.2 1942.02   555.1 1924.17     585 1896.82
   614.9 1895.24   674.7 1897.25   777.6 1894.71   784.4 1894.52   792.6 1895.13
   869.1 1905.58     884 1909.61     899 1917.29   928.9 1924.46   983.7 1951.06
  1033.6 1965.06  1113.4 2002.58  1193.3 2034.71  1223.2 2044.56  1313.1  2067.5
    1358 2080.66    1388 2091.75  1412.9 2094.98  1457.8 2108.45  1497.8 2113.46
#Mann= 3 , 0 , 0
       0      .1       0   777.6    .045       0   792.6      .1       0
Bank Sta=777.6,792.6
XS Rating Curve= 0 ,0
Exp/Cntr=0.3,0.1

Type RM Length L Ch R = 1 ,7604.1  ,92.5,92.8,93.2
XS GIS Cut Line= 4
     1858753.924      179875.101     1858609.121      180533.294
     1858938.218      180901.882     1859277.187      181178.323
#Sta/Elev= 30
       0 2117.26    74.9 2102.34   109.8 2107.96   149.8  2107.8   259.6 2085.04
   344.4 2052.17   394.4 2025.25   424.3 2011.38   474.2 1991.96   509.2  1980.9
   574.1    1951   673.9  1920.7   718.8 1892.68     989 1891.29   998.4  1889.6
    1004 1889.76  1033.3 1899.89  1088.2 1928.98  1113.2 1944.29  1143.1 1968.31
  1187.9 1985.88  1317.2 2000.79    1342 2009.03  1366.9 2014.27  1421.6  2038.8
  1451.4    2038  1486.2 2042.12    1521 2053.28  1560.7 2052.79  1605.5 2062.69
#Mann= 3 , 0 , 0
       0      .1       0     989    .045       0    1004      .1       0
Bank Sta=989,1004
XS Rating Curve= 0 ,0
Exp/Cntr=0.3,0.1