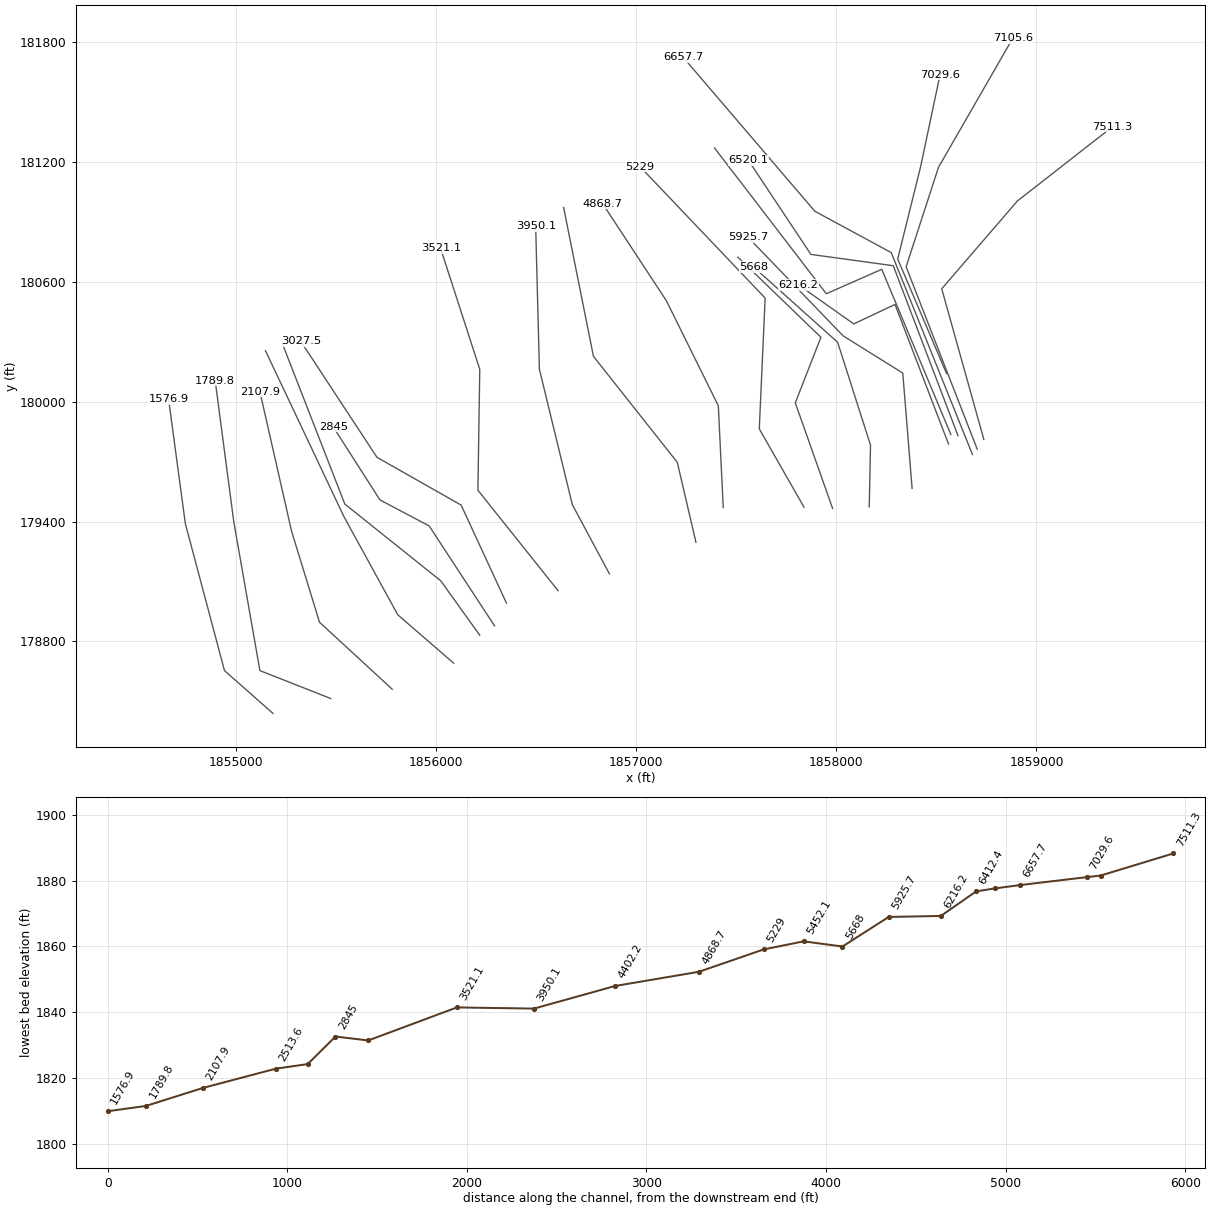
HEC-RAS study BeartownFk.prj: BeartownFk

--- BeartownFk.g01 (geometry) --- (continued)

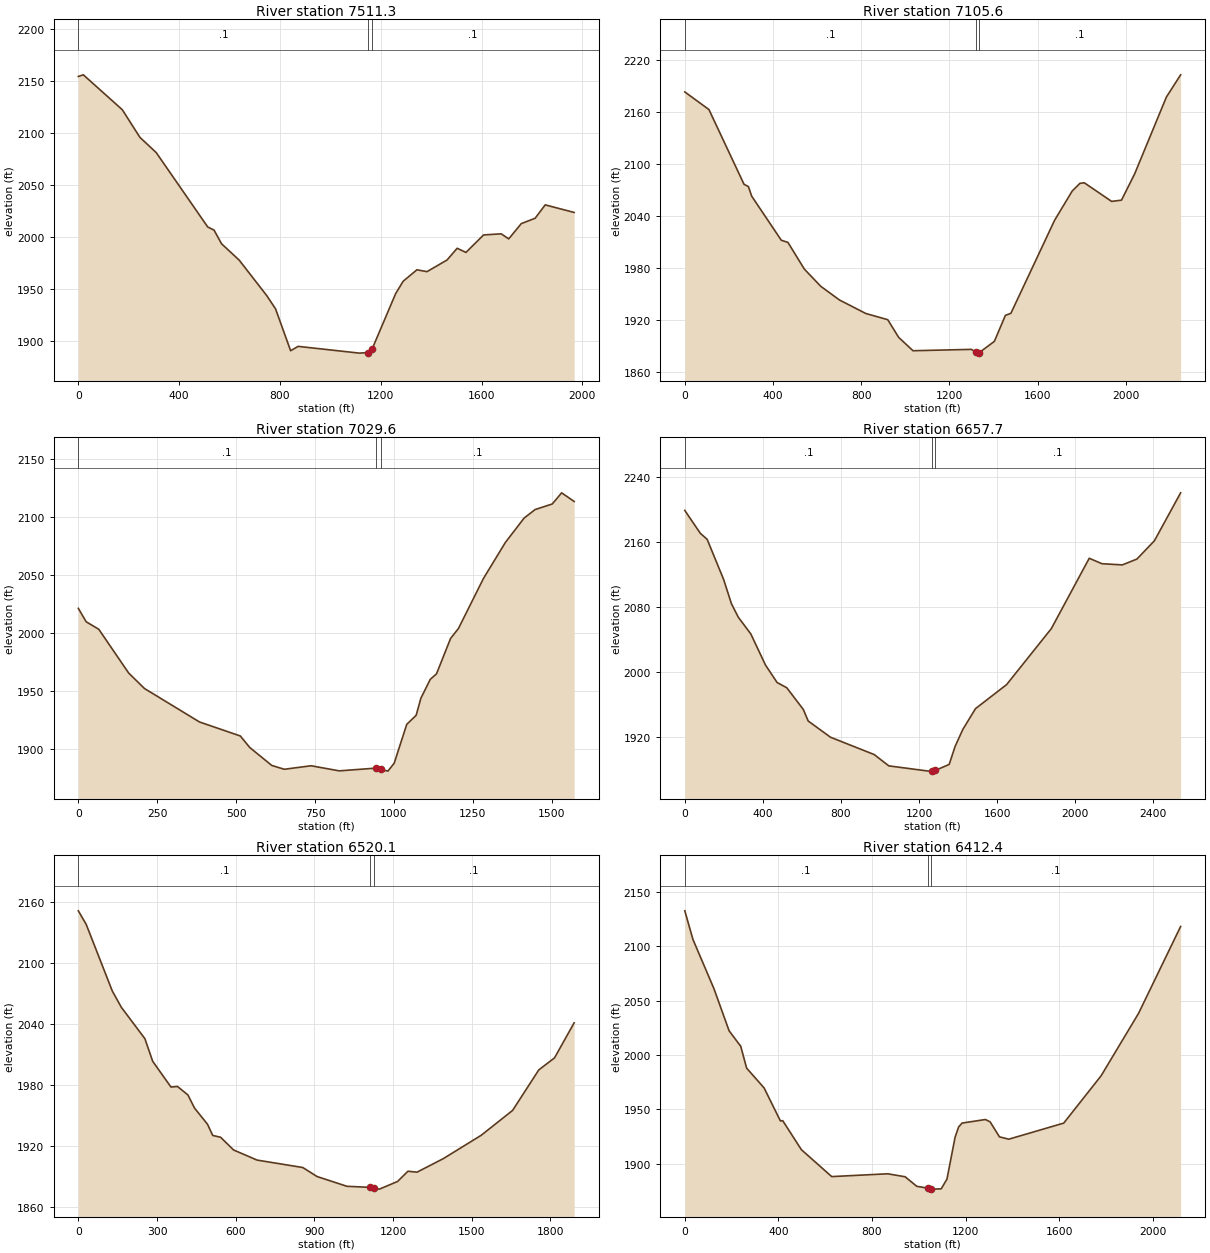
Type RM Length L Ch R = 1 ,7511.3  ,397.1,405.7,414
XS GIS Cut Line= 4
     1858736.984      179811.939     1858526.658      180565.875
     1858905.245      181005.941     1859380.904      181378.055
#Sta/Elev= 30
       0 2153.97    19.9 2155.54   174.5 2122.02   244.3  2095.5   309.1 2080.83
   513.5 2009.38   538.4 2006.42   568.4 1993.22   638.1  1977.6   747.8 1943.42
   782.7 1930.64   842.3 1890.53     872 1894.72  1115.2 1888.23  1150.7 1888.76
  1165.7 1892.25    1259  1945.4  1288.8 1957.28  1343.4 1968.27  1383.2 1966.48
    1463  1977.7    1503 1988.94  1537.9 1984.96  1607.8 2001.75  1677.7 2002.82
  1707.6 1997.98  1757.5 2012.64  1812.4 2017.78  1852.4 2030.63  1967.2 2023.35
#Mann= 3 , 0 , 0
       0      .1       0  1150.7    .045       0  1165.7      .1       0
Bank Sta=1150.7,1165.7
XS Rating Curve= 0 ,0
Exp/Cntr=0.3,0.1

Type RM Length L Ch R = 1 ,7105.6  ,74.7,76,77.4
XS GIS Cut Line= 4
     1858704.195      179762.344      1858348.69      180675.891
     1858510.479      181174.201     1858881.515      181820.273
#Sta/Elev= 30
       0 2182.76   109.5 2162.41   268.7 2076.21   288.6 2073.57   303.5 2062.51
   437.9 2011.64   467.8 2009.23   542.4 1978.38     617 1958.52   701.6  1942.8
     821 1927.22   920.6 1920.07   970.3 1899.65  1035.2 1884.26  1299.6 1885.83
  1320.9 1882.69  1329.6  1881.5  1335.9  1882.1  1404.4  1895.1  1454.3 1925.05
  1479.2  1927.4    1678 2034.94  1757.5 2068.48  1792.3 2077.28  1812.2 2077.96
  1936.3 2056.48    1981 2057.93  2040.6 2088.18  2184.7 2176.86  2249.2 2202.46
#Mann= 3 , 0 , 0
       0      .1       0  1320.9    .045       0  1335.9      .1       0
Bank Sta=1320.9,1335.9
XS Rating Curve= 0 ,0
Exp/Cntr=0.3,0.1

Type RM Length L Ch R = 1 ,7029.6  ,341.1,371.9,402.4
XS GIS Cut Line= 4
     1858550.788       180141.65     1858306.625      180714.721
     1858421.244      181178.004     1858518.402      181638.605
#Sta/Elev= 30
       0  2021.2    24.9 2009.63    64.8 2003.18   159.5  1965.5   209.3 1952.23
   383.7 1923.38   513.3 1911.29   543.2 1901.35     613  1885.9   652.7 1882.63
   737.3 1885.65   826.7 1881.26   943.6 1883.64   958.6 1882.62   980.8 1881.03
  1000.7 1887.83  1040.5  1921.3  1070.3  1929.1  1085.2 1943.73    1115 1960.05
  1134.8 1964.81  1179.4 1995.29  1204.2  2003.8  1283.5 2046.91  1352.9 2077.91
  1412.3  2098.9    1447 2106.24  1501.5 2111.07  1531.3 2120.67  1570.9 2113.24
#Mann= 3 , 0 , 0
       0      .1       0   943.6    .045       0   958.6      .1       0
Bank Sta=943.6,958.6
XS Rating Curve= 0 ,0
Exp/Cntr=0.3,0.1

Type RM Length L Ch R = 1 ,6657.7  ,129.3,137.6,145.3
XS GIS Cut Line= 4
     1858680.372      179735.464     1858274.268      180747.079
     1857892.446      180954.168     1857232.925      181727.133
#Sta/Elev= 30
       0 2198.44    79.6 2170.34   114.5 2163.01   199.1 2113.69   238.9 2084.04
   273.8 2067.58   338.5 2046.83   413.1 2008.92   472.9 1987.36   522.6 1980.88
   607.3 1954.27   632.2 1940.13   746.6  1920.2   970.6 1898.94  1045.3 1885.07
  1249.8 1878.62  1268.9    1879  1283.9 1879.52  1354.7 1886.86  1384.7 1908.78
  1424.6 1929.81  1489.5 1955.28    1649 1984.79  1878.1 2053.48  2072.3 2139.77
  2137.1 2133.08  2241.7 2131.62  2316.4 2138.75  2406.1 2161.18  2540.5 2220.03
#Mann= 3 , 0 , 0
       0      .1       0  1268.9    .045       0  1283.9      .1       0
Bank Sta=1268.9,1283.9
XS Rating Curve= 0 ,0
Exp/Cntr=0.3,0.1

Type RM Length L Ch R = 1 ,6520.1  ,95.1,107.8,120.8
XS GIS Cut Line= 4
     1858607.963      179830.152     1858284.503      180681.418
     1857872.739      180738.043     1857560.825      181208.698
#Sta/Elev= 30
       0 2150.96    29.9 2137.73   129.4 2072.31   164.2 2056.15   253.8 2025.44
   283.6 2003.19   353.3 1977.88   378.2 1978.44     418 1970.14   442.9 1957.33
   492.6 1941.37   512.6 1930.35   542.4  1928.6   592.2 1916.08   681.7 1906.15
   855.9 1898.86   910.6 1889.98  1024.4 1880.41  1113.7 1879.35  1128.7 1878.72
  1148.2 1877.63  1217.4 1885.14    1257 1895.21  1291.6 1894.28  1391.2 1907.48
  1536.2 1930.47  1656.1 1954.92    1756 1994.71    1816 2006.52  1890.9 2040.98
#Mann= 3 , 0 , 0
       0      .1       0  1113.7    .045       0  1128.7      .1       0
Bank Sta=1113.7,1128.7
XS Rating Curve= 0 ,0
Exp/Cntr=0.3,0.1

Type RM Length L Ch R = 1 ,6412.4  ,195.6,196.2,196.8
XS GIS Cut Line= 4
     1858572.379      179835.782     1858226.928      180663.426
     1857949.847      180541.078     1857391.264      181270.744
#Sta/Elev= 30
       0 2132.59    34.9 2106.24   124.6    2061   189.3 2022.29   239.2 2007.96
   264.1 1987.98   338.8 1969.78   408.6 1939.37   418.5 1939.64   498.2 1912.96
   627.8 1888.21     867 1890.79   941.5 1888.06   991.2  1879.3  1037.7 1877.59
  1052.7 1876.72  1055.7 1876.69  1095.5 1876.93  1120.3 1885.93    1155 1924.46
  1169.9 1933.76  1184.8 1937.42  1284.6  1940.7  1304.6 1938.58  1344.6 1924.76
  1384.5 1922.61  1619.2  1937.4  1779.1 1980.95  1938.9 2038.29  2118.7 2118.19
#Mann= 3 , 0 , 0
       0      .1       0  1037.7    .045       0  1052.7      .1       0
Bank Sta=1037.7,1052.7
XS Rating Curve= 0 ,0
Exp/Cntr=0.3,0.1

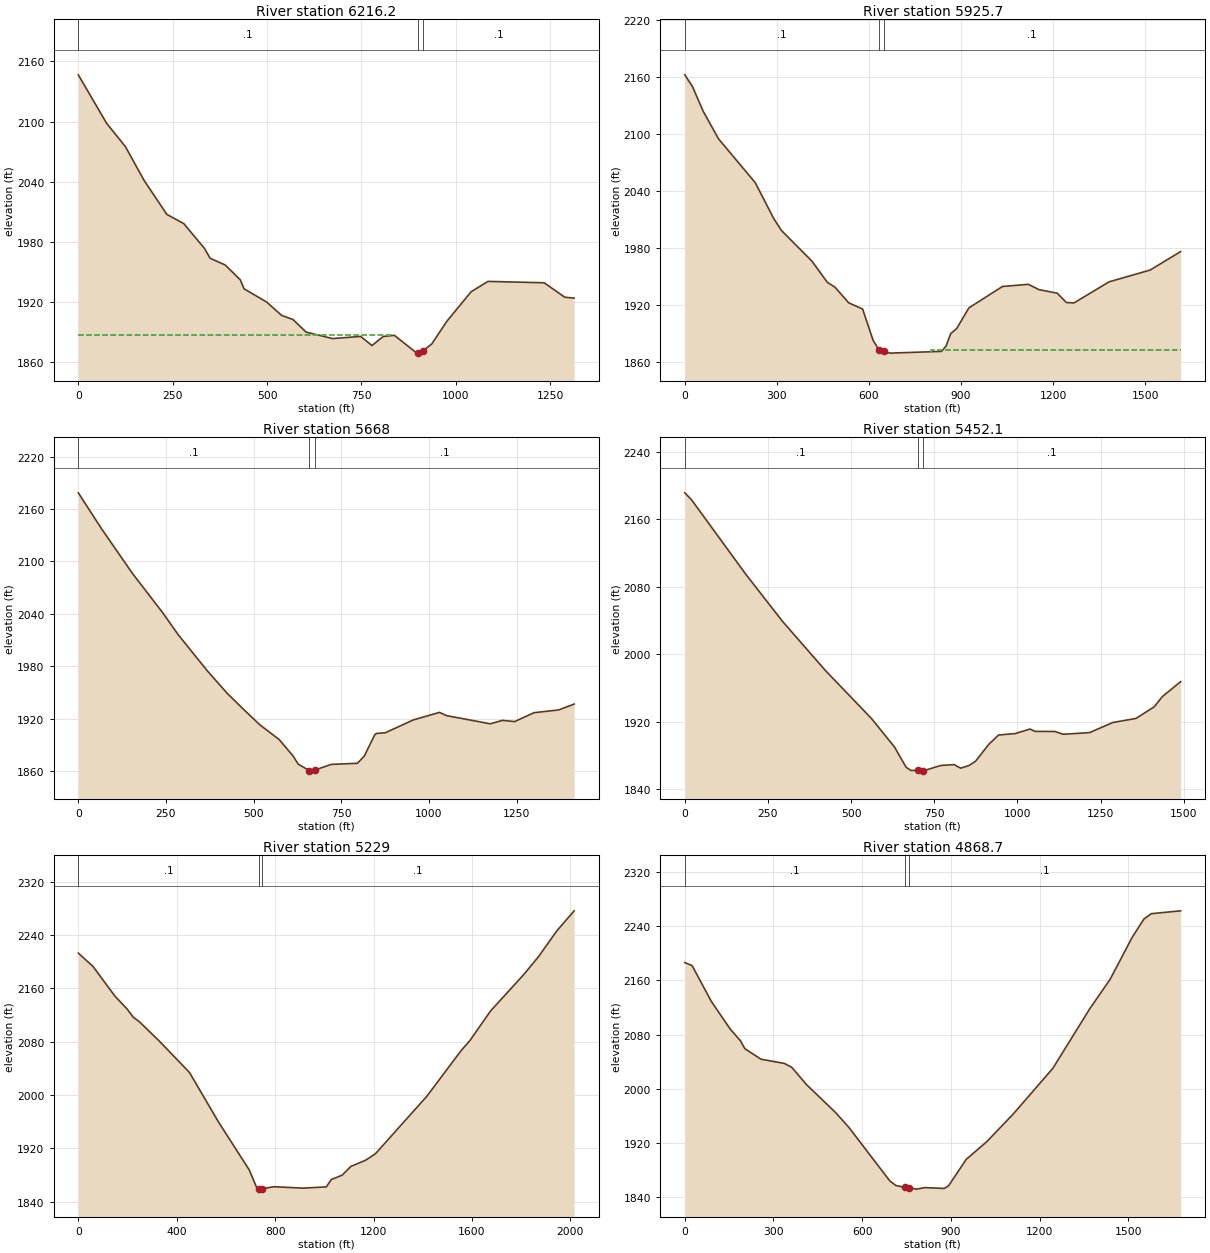
Type RM Length L Ch R = 1 ,6216.2  ,313.3,290.5,267.7
XS GIS Cut Line= 4
     1858560.619      179788.378     1858293.265      180487.398
     1858087.179      180389.925      1857811.47      180584.871
#Sta/Elev= 30
       0 2146.56    74.8 2098.36   124.7 2075.04   174.6 2041.13   234.5 2007.51
   279.4  1998.3   334.3 1973.62   349.2 1963.78   389.2 1957.07   429.1 1942.38
   439.1 1933.36   498.9 1920.19   538.8 1906.85   568.8 1902.75   603.7 1890.18
   673.6 1883.75   748.4 1885.88   778.1 1876.75   807.9 1885.82   837.6 1886.98
   897.1 1869.24   899.3  1869.4   914.3 1871.82   936.7 1878.41   976.4 1900.85
  1040.9  1930.4  1085.6 1940.73  1234.6 1939.33  1289.2 1924.95    1314 1924.08
#Mann= 3 , 0 , 0
       0      .1       0   899.3    .045       0   914.3      .1       0
#XS Ineff= 2 , 0
          828.41 1887.09
Permanent Ineff=
       F       F
Bank Sta=899.3,914.3
XS Rating Curve= 0 ,0
Exp/Cntr=0.3,0.1

Type RM Length L Ch R = 1 ,5925.7  ,273.6,257.6,241.7
XS GIS Cut Line= 4
     1858378.556      179566.269     1858331.985      180143.741
     1858033.935      180330.023     1857558.917      180823.668
#Sta/Elev= 30
       0 2162.41      25 2150.06    59.9 2124.01   109.9 2094.93   229.7 2048.65
   289.7 2010.98   314.6  1998.4   414.5 1965.91   464.5 1943.59   489.4 1938.49
   534.4 1921.94   579.4 1915.51     614 1882.22   633.2 1872.24   648.2 1871.14
   668.4 1868.94   836.8 1870.77   851.6 1876.51   866.5 1889.44   886.3 1894.96
   925.9 1916.67  1035.1 1939.19  1119.5 1941.51  1154.2 1935.91  1213.8 1932.15
  1243.6 1922.31  1268.4  1921.9  1382.6  1944.1  1516.6 1956.56  1615.9 1976.02
#Mann= 3 , 0 , 0
       0      .1       0   633.2    .045       0   648.2      .1       0
#XS Ineff= 2 , 0
                           803.5         1871.83
Permanent Ineff=
       F       F
Bank Sta=633.2,648.2
XS Rating Curve= 0 ,0
Exp/Cntr=0.3,0.1

Type RM Length L Ch R = 1 ,5668    ,231.7,215.9,200.2
XS GIS Cut Line= 4
     1858164.332      179473.128     1858170.727      179782.808
     1858006.416      180298.022      1857586.86      180674.643
#Sta/Elev= 30
       0  2178.5      65  2138.1   154.9 2085.97   239.8 2041.77   284.8 2016.13
   369.3  1974.1   423.9 1949.36   473.5  1929.8   518.1 1912.88   572.7 1896.21
   612.4 1877.36   627.3 1867.93   658.8 1860.57     667 1859.96   673.8 1861.06
   721.5 1867.69     796  1868.9   815.8 1877.26   845.6 1901.72   850.5 1903.09
   875.5 1903.85   955.3 1918.54  1030.1  1927.2  1050.1  1923.5  1174.8 1914.14
  1209.8 1918.03  1244.7 1916.69  1299.6 1926.84  1369.4 1929.96  1414.3 1936.68
#Mann= 3 , 0 , 0
       0      .1       0   658.8    .045       0   673.8      .1       0
Bank Sta=658.8,673.8
XS Rating Curve= 0 ,0
Exp/Cntr=0.3,0.1

Type RM Length L Ch R = 1 ,5452.1  ,215.2,223.1,231
XS GIS Cut Line= 4
     1857981.351      179465.324      1857794.76      179994.463
     1857922.868      180323.086     1857507.911      180724.118
#Sta/Elev= 30
       0 2191.25    19.9 2183.19   183.7 2094.64     293 2039.38     422  1981.1
   561.1 1923.95   630.6  1890.1   665.4 1866.16   680.3 1862.27   700.3  1862.5
   710.1 1861.53   715.3 1861.66   769.7 1868.23   809.5 1869.28   829.3 1865.03
   854.2 1868.09     874 1873.14   913.8 1893.18   943.6 1904.32   993.4 1905.99
  1038.2 1911.42  1053.1 1908.61  1112.8 1908.52  1137.6 1905.19  1217.2 1907.19
  1286.9 1919.13  1356.5 1923.96  1411.3 1937.65  1436.1 1949.88  1490.9 1967.53
#Mann= 3 , 0 , 0
       0      .1       0   700.3    .045       0   715.3      .1       0
Bank Sta=700.3,715.3
XS Rating Curve= 0 ,0
Exp/Cntr=0.3,0.1

Type RM Length L Ch R = 1 ,5229    ,349.4,360.3,371.2
XS GIS Cut Line= 4
     1857838.278      179471.896     1857614.802      179864.319
     1857643.979      180519.488     1857018.702      181177.603
#Sta/Elev= 30
       0 2212.95    59.6    2193   148.9 2148.38   198.5 2129.01   223.3 2116.83
   248.1 2110.06   327.5 2081.66   451.6 2034.05   570.8 1959.09     695 1887.69
   724.8 1861.41   732.4 1859.23   734.8 1859.07   747.4  1859.6   794.4 1862.69
   913.6 1860.56    1008 1862.46  1027.9 1873.42  1072.6 1880.07  1107.4 1893.07
  1167.3 1902.39  1207.2    1912  1416.7 1998.39  1556.3 2067.04  1591.2 2081.65
    1676 2126.45  1810.7 2180.94  1870.6 2207.71  1945.4 2246.62  2015.2 2276.33
#Mann= 3 , 0 , 0
       0      .1       0   732.4    .045       0   747.4      .1       0
Bank Sta=732.4,747.4
XS Rating Curve= 0 ,0
Exp/Cntr=0.3,0.1

Type RM Length L Ch R = 1 ,4868.7  ,461.8,466.5,470.6
XS GIS Cut Line= 4
     1857434.644      179470.139      1857410.08       179979.72
     1857150.992      180505.094      1856832.42      180991.321
#Sta/Elev= 30
       0 2186.42    24.8 2181.94    89.2 2129.58   153.6 2088.35   188.2 2071.14
   203.1 2059.47   257.6 2043.93   336.8 2037.71   361.6 2032.07   411.1 2006.72
   510.2  1965.2   554.8 1943.49   693.8 1864.29   713.7 1857.72   743.9 1854.92
   758.9 1854.24   783.2 1852.29     813 1854.52   877.5  1853.3   892.4 1857.35
     952 1896.19  1021.5 1922.28  1110.9 1963.04    1245 2030.46  1369.2 2117.88
  1438.8 2161.81  1513.3 2223.61    1553 2250.65  1577.9 2258.56  1677.2 2262.76
#Mann= 3 , 0 , 0
       0      .1       0   743.9    .045       0   758.9      .1       0
Bank Sta=743.9,758.9
XS Rating Curve= 0 ,0
Exp/Cntr=0.3,0.1

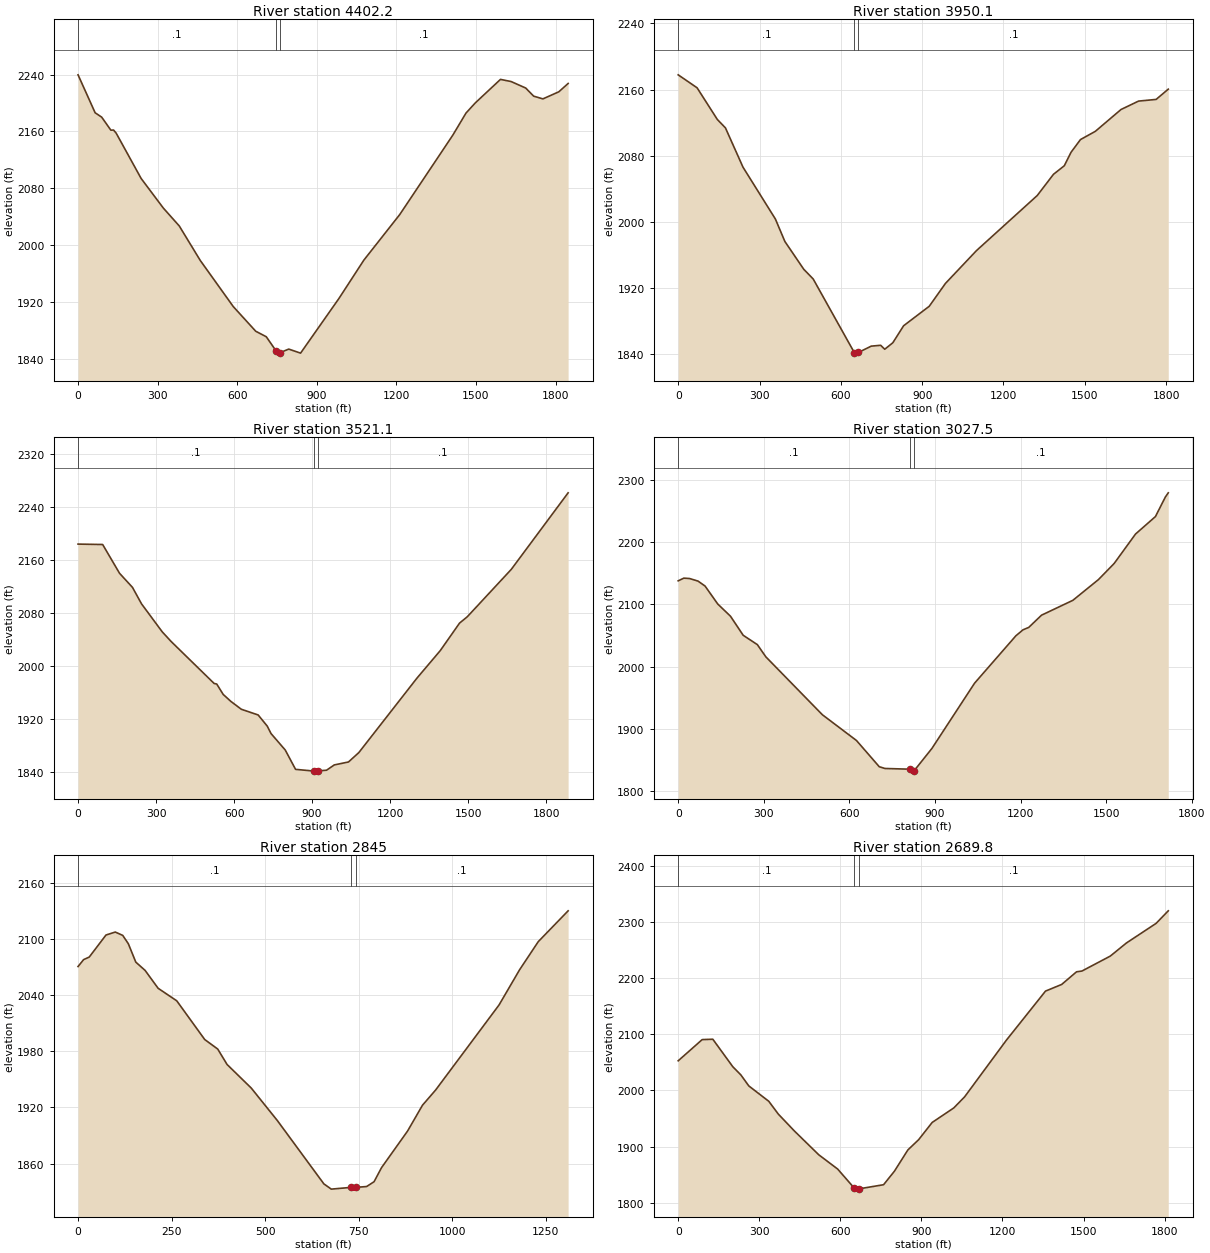
Type RM Length L Ch R = 1 ,4402.2  ,461.8,452.1,442.4
XS GIS Cut Line= 4
     1857298.124      179296.161     1857204.983      179696.666
      1856785.85      180227.568     1856636.825      180972.693
#Sta/Elev= 30
       0 2239.76    64.4 2186.37    89.2 2180.14   123.8 2161.83   133.8 2162.05
   143.7 2157.69   237.8 2093.88     322 2051.98   381.5 2027.07   460.9 1978.37
   585.3 1913.45   669.8 1878.82   709.6 1871.03   746.9 1850.93   761.9 1848.67
   794.2 1853.67   838.9 1847.98   983.2 1924.75  1077.6 1978.97  1212.6 2042.98
  1412.6 2154.71  1462.5 2185.92  1497.5 2200.22  1592.5 2233.33  1632.5 2230.32
  1687.5 2221.19  1717.5 2209.76  1752.5 2205.89  1812.5 2215.88  1847.5 2227.59
#Mann= 3 , 0 , 0
       0      .1       0   746.9    .045       0   761.9      .1       0
Bank Sta=746.9,761.9
XS Rating Curve= 0 ,0
Exp/Cntr=0.3,0.1

Type RM Length L Ch R = 1 ,3950.1  ,434.7,429,423.4
XS GIS Cut Line= 4
     1856865.667      179138.022     1856680.173      179485.056
     1856515.742      180162.369     1856497.114      180879.553
#Sta/Elev= 30
       0 2177.88    69.7 2162.19   144.4 2123.84   174.3  2113.7   239.1 2066.11
   358.6 2003.39   393.5 1976.24   463.2  1942.6     498 1930.84   649.7 1841.77
   652.4 1841.11   664.7 1841.89   712.1 1849.57     747 1850.58   761.9 1845.82
   791.8 1853.66   831.6 1874.24   926.2 1897.83   985.9 1925.46  1100.4 1965.17
  1324.6 2031.85  1384.4 2057.49  1424.3 2067.84  1449.2 2084.14  1484.1 2099.55
  1538.9 2109.51  1633.5  2135.9  1698.3  2146.1  1763.1 2148.12  1807.9 2160.53
#Mann= 3 , 0 , 0
       0      .1       0   649.7    .045       0   664.7      .1       0
#XS Ineff= 2 , 0
                          746.85         1850.56
Permanent Ineff=
       F       F
Bank Sta=649.7,664.7
XS Rating Curve= 0 ,0
Exp/Cntr=0.3,0.1

Type RM Length L Ch R = 1 ,3521.1  ,468.7,493.6,518.4
XS GIS Cut Line= 4
     1856608.883      179053.995     1856208.378      179556.955
     1856217.692      180162.369     1856022.096      180767.784
#Sta/Elev= 30
       0  2184.5    94.7 2183.87   159.5 2140.43   209.3 2119.12   244.2  2094.2
     324  2051.8   358.8 2037.02   523.3 1973.94   533.3 1973.07   558.2 1957.35
   588.1 1946.69     628 1934.93   692.6 1926.34   727.3 1909.65   742.2 1898.22
   796.8 1873.36   836.5 1844.15   907.6 1841.53   910.9 1841.47   922.6 1841.75
   955.6 1842.85   985.4 1850.85    1040  1855.3  1079.7 1869.46  1303.1 1981.89
  1392.6  2023.4  1467.1 2065.12    1497 2074.78    1666  2146.3  1884.6 2261.97
#Mann= 3 , 0 , 0
       0      .1       0   907.6    .045       0   922.6      .1       0
Bank Sta=907.6,922.6
XS Rating Curve= 0 ,0
Exp/Cntr=0.3,0.1

Type RM Length L Ch R = 1 ,3027.5  ,181.6,182.5,183.4
XS GIS Cut Line= 4
     1856350.897      178992.039     1856124.551      179482.442
     1855703.796      179721.757     1855323.541       180302.08
#Sta/Elev= 30
       0 2138.05    19.8 2142.36    39.6 2141.82    69.4 2137.64    94.2 2129.64
   138.8 2100.65   183.3 2081.03   227.9  2050.3   277.5 2035.28   307.2 2015.63
   505.4 1922.31     625 1880.79   704.8 1838.56   724.8 1835.71   811.3 1834.58
   824.6 1831.44   826.3 1831.59   889.4 1867.96  1039.1 1973.21  1183.9 2049.54
  1208.8 2059.12  1228.8 2062.99  1273.7  2082.7  1383.6 2106.66  1473.4 2140.12
  1528.3    2166  1603.2 2213.43    1673 2241.58    1708 2273.25    1718 2279.84
#Mann= 3 , 0 , 0
       0      .1       0   811.3    .045       0   826.3      .1       0
Bank Sta=811.3,826.3
XS Rating Curve= 0 ,0
Exp/Cntr=0.3,0.1

Type RM Length L Ch R = 1 ,2845    ,159.4,155.1,150.9
XS GIS Cut Line= 4
     1856291.321      178877.919     1855964.775      179378.071
     1855718.832      179508.276     1855485.289      179874.091
#Sta/Elev= 30
       0  2070.5    14.9 2077.89    29.9 2080.62    74.7 2104.18    99.6 2107.35
   119.5 2103.74   134.4 2094.86   154.3 2075.23   179.2 2066.36     214 2047.26
   263.8 2033.86   338.5 1992.51   373.3 1982.31   398.2 1965.85   462.9 1940.62
   532.6  1905.9     657 1838.19   676.8 1832.63   728.7 1834.47   743.7 1834.54
   771.2 1835.41   791.1 1840.57     811 1855.58   880.6 1894.71   920.5 1922.34
   955.4 1938.47    1125 2029.42  1179.9 2067.03  1229.8 2097.08  1309.6 2130.03
#Mann= 3 , 0 , 0
       0      .1       0   728.7    .045       0   743.7      .1       0
Bank Sta=728.7,743.7
XS Rating Curve= 0 ,0
Exp/Cntr=0.3,0.1

Type RM Length L Ch R = 1 ,2689.8  ,180.4,176.2,200.4
XS GIS Cut Line= 4
     1856217.692      178830.458     1856022.644      179103.194
     1855543.158      179487.609     1855230.401      180292.766
#Sta/Elev= 30
       0 2052.69    88.8 2090.44   128.2 2091.08   202.2 2042.11   231.8 2027.66
   261.3 2008.01   335.3  1980.6   370.3 1957.95   430.2 1927.69   520.2 1885.41
   590.1 1860.02   652.4 1825.65   660.1 1824.26   667.4 1824.65     760  1832.1
     800 1856.03   849.9 1893.97   889.9 1912.34   939.9 1942.95  1019.8 1968.78
  1059.7  1988.4  1214.5  2089.4  1359.3 2176.78  1419.2 2188.64  1474.1 2211.12
  1494.1 2212.49  1598.9 2239.05  1658.8 2262.45  1768.7 2297.38  1813.6 2319.68
#Mann= 3 , 0 , 0
       0      .1       0   652.4    .045       0   667.4      .1       0
Bank Sta=652.4,667.4
XS Rating Curve= 0 ,0
Exp/Cntr=0.3,0.1

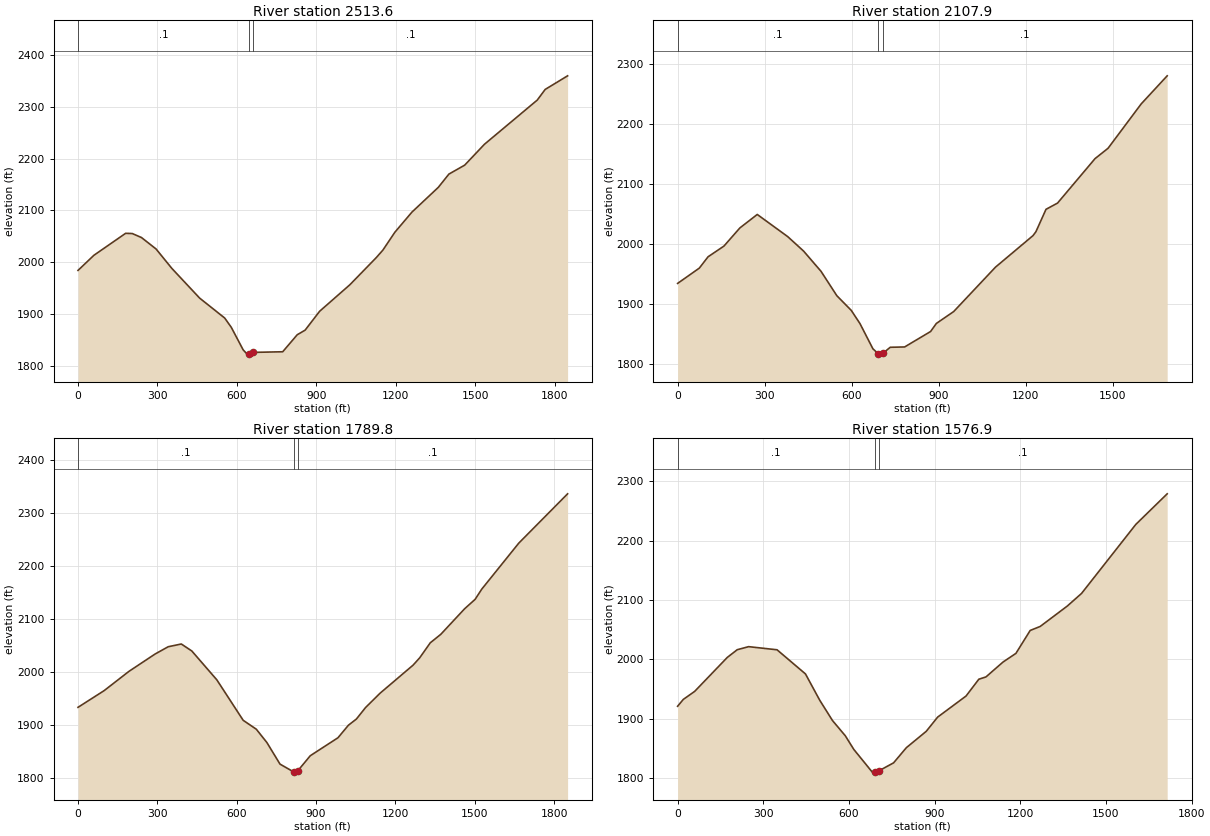
Type RM Length L Ch R = 1 ,2513.6  ,416.6,405.8,366.5
XS GIS Cut Line= 4
     1856087.295      178690.747     1855807.873      178932.912
     1855537.765      179426.558     1855146.574       180255.51
#Sta/Elev= 30
       0 1984.36      60 2013.51   179.9 2055.92   204.9 2055.48   239.8 2047.72
   294.8 2025.67   354.8    1988   459.4 1930.92     554  1892.5   578.9 1874.59
   623.7 1831.16   638.7 1822.88   647.4 1824.05   662.4 1826.25   773.1 1827.44
   827.9 1860.22   857.8 1869.16   912.6 1905.55  1027.1 1956.85  1126.8 2009.22
  1151.7 2023.66  1196.5 2057.84  1261.3 2096.86  1360.9  2144.6  1400.7 2170.09
  1460.5 2187.42  1535.2 2227.72  1734.5  2312.9  1764.4  2333.4  1849.1 2359.68
#Mann= 3 , 0 , 0
       0      .1       0   647.4    .045       0   662.4      .1       0
Bank Sta=647.4,662.4
XS Rating Curve= 0 ,0
Exp/Cntr=0.3,0.1

Type RM Length L Ch R = 1 ,2107.9  ,321,318.1,315.2
XS GIS Cut Line= 4
     1855779.931       178560.35     1855416.682      178895.656
     1855276.971      179352.045     1855118.632      180050.601
#Sta/Elev= 30
       0 1934.74    74.9 1960.19   104.9 1978.99   159.8 1996.87   214.7 2027.07
   274.6 2049.46   379.5 2012.64   434.4  1988.5   494.4 1954.88     549 1914.24
   598.8 1889.78   628.6 1867.97   673.3 1825.94   692.3 1817.43   698.2 1817.04
   707.3 1818.21     733 1828.42   782.7 1828.98   872.2 1854.67   892.1  1868.1
   951.8 1887.88    1096 1961.81  1225.3 2014.26  1235.3 2020.74  1270.1 2058.01
  1309.9 2068.41  1439.2 2142.42    1484  2159.6  1598.4  2233.5  1687.9 2280.18
#Mann= 3 , 0 , 0
       0      .1       0   692.3    .045       0   707.3      .1       0
Bank Sta=692.3,707.3
XS Rating Curve= 0 ,0
Exp/Cntr=0.3,0.1

Type RM Length L Ch R = 1 ,1789.8  ,210.9,212.9,214.9
XS GIS Cut Line= 4
     1855472.566      178513.779     1855118.632       178653.49
     1854988.235      179398.616     1854895.094      180106.485
#Sta/Elev= 30
       0  1933.6    98.8 1965.05   192.7 2001.37   291.6 2034.05     341 2047.69
   390.5 2052.84   430.3 2039.68   524.8 1985.38   624.4 1909.16   674.1 1892.35
     714 1867.32   763.7 1826.64   815.2    1812   818.5 1811.56   830.2 1813.66
   878.2 1842.48   982.7 1876.25  1022.5 1899.99  1052.4 1911.51  1087.2 1933.26
    1142  1960.2  1266.8 2013.05  1291.7 2026.78  1331.7 2055.06  1371.6 2071.12
  1461.5 2119.15  1501.4 2137.02  1526.4 2156.18  1666.2 2242.72  1850.9 2335.66
#Mann= 3 , 0 , 0
       0      .1       0   815.2    .045       0   830.2      .1       0
Bank Sta=815.2,830.2
XS Rating Curve= 0 ,0
Exp/Cntr=0.3,0.1

Type RM Length L Ch R = 1 ,1576.9  ,274.7,270.6,266.3
XS GIS Cut Line= 4
      1855183.83      178439.267     1854941.664       178653.49
     1854746.069      179389.302     1854662.242      180013.344
#Sta/Elev= 30
       0 1920.88    19.9  1932.4    59.7 1945.91   174.1  2003.2   208.9 2016.14
   248.7 2021.25   348.2 2015.98   447.7 1975.34   497.5 1931.19   542.3 1896.84
   587.1 1871.24   616.9 1848.25   681.6 1809.95   690.3 1810.46   705.3 1812.25
   756.2 1825.56     801 1851.11   870.7 1878.71   910.5 1902.58    1010 1938.12
  1054.8 1966.42  1079.7 1970.28  1139.6 1995.39  1184.6 2009.93  1234.6 2048.56
  1269.6 2055.28  1364.5 2089.63  1414.5 2110.93  1604.4 2227.11  1714.3 2278.64
#Mann= 3 , 0 , 0
       0      .1       0   690.3    .045       0   705.3      .1       0
Bank Sta=690.3,705.3
XS Rating Curve= 0 ,0
Exp/Cntr=0.3,0.1