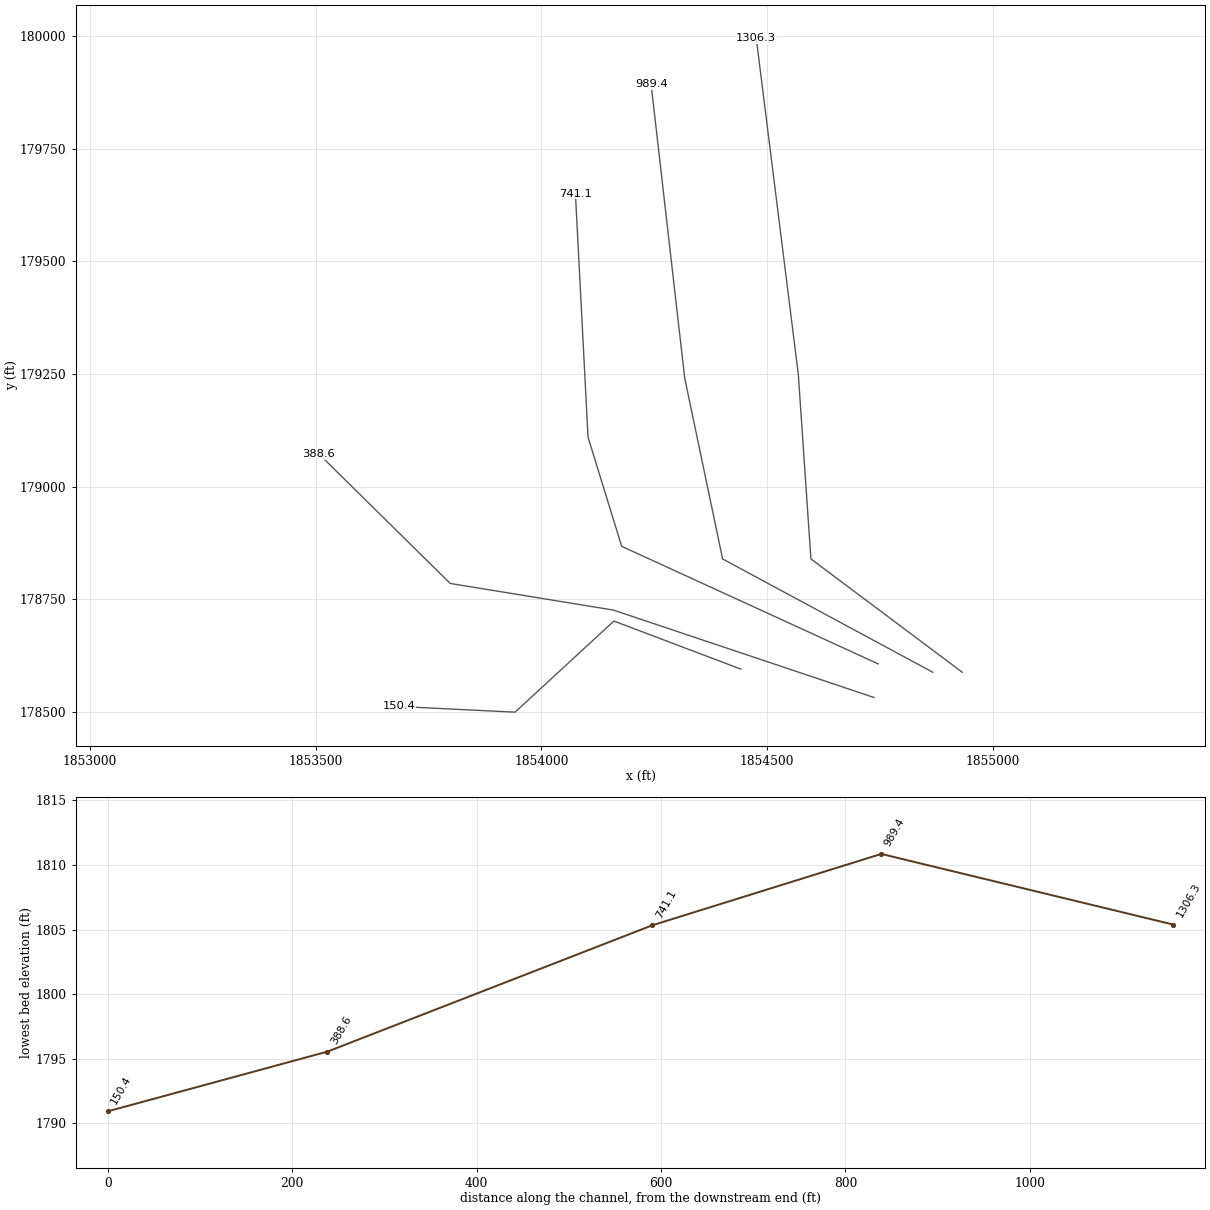
HEC-RAS study BeartownFk.prj: BeartownFk

--- BeartownFk.g01 (geometry) --- (continued)

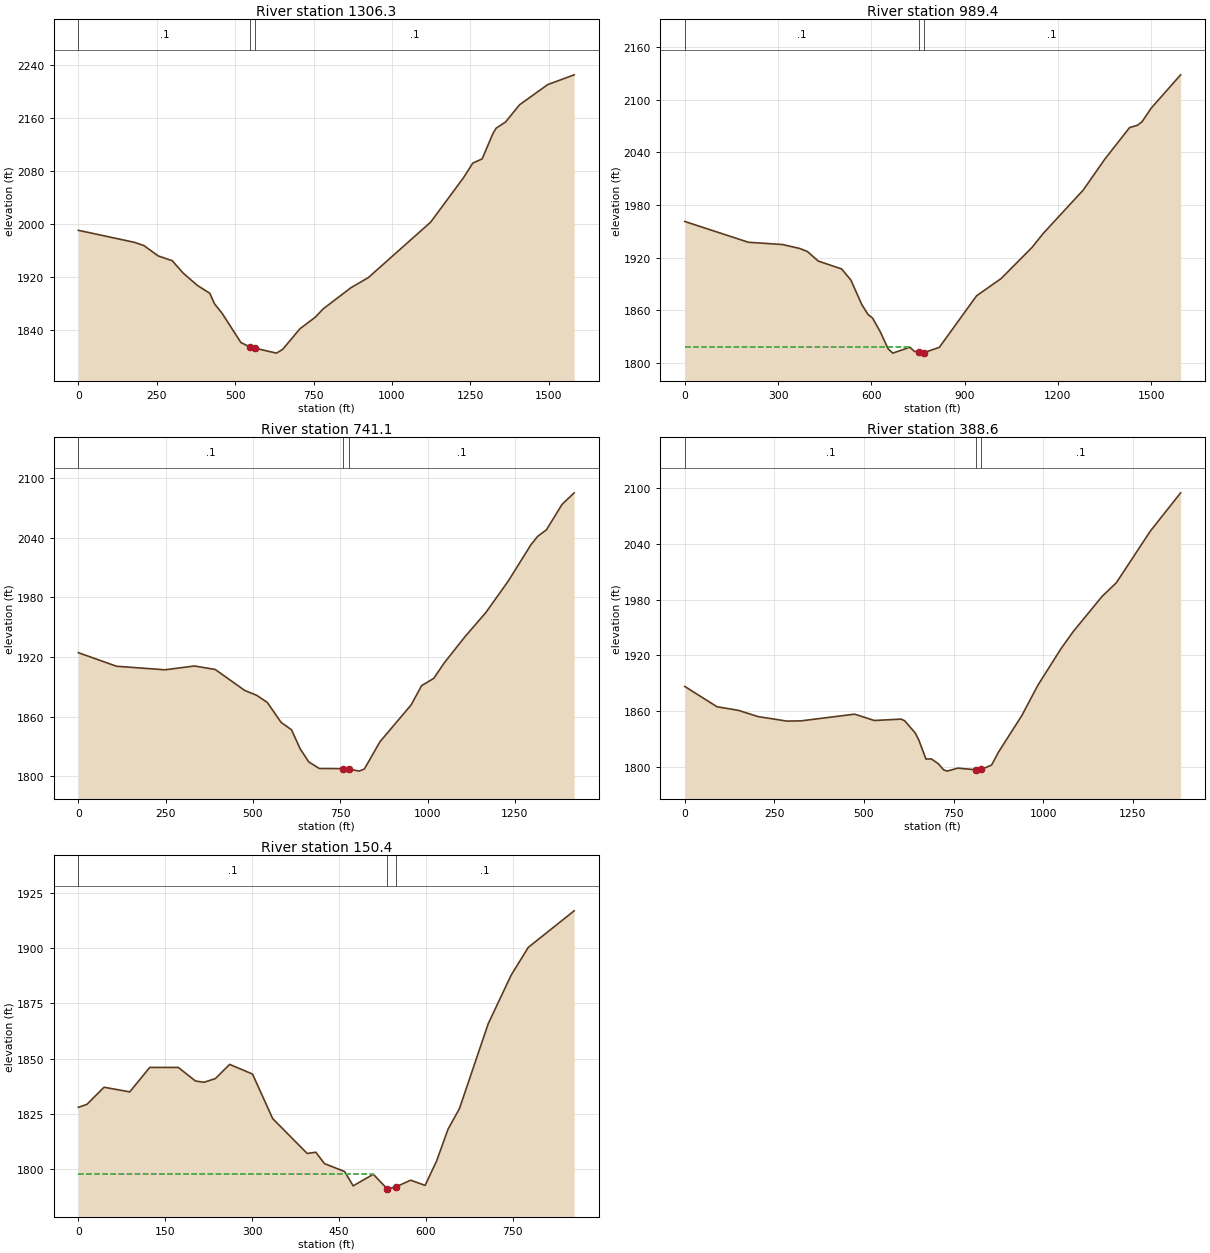
Type RM Length L Ch R = 1 ,1306.3  ,317.1,316.9,361.1
XS GIS Cut Line= 4
      1854932.35      178588.292     1854597.044      178839.772
     1854569.102      179249.591     1854475.961      179994.716
#Sta/Elev= 30
       0 1990.43   179.6 1972.21   209.6  1967.3   254.5 1951.84   299.4 1944.64
   334.3 1925.92   379.2 1907.55   419.1 1895.56     434 1879.83   458.7 1865.16
   518.1  1821.5   548.8  1814.2   563.8 1812.78   631.9 1805.39   651.7 1811.18
   706.2 1841.95   755.7 1859.62   780.4 1871.97   869.7 1904.13   924.4 1919.12
  1123.3 2002.71  1227.7 2069.46  1257.6 2091.66  1287.4 2097.96  1322.2 2136.59
  1332.2  2144.3    1362 2153.52  1406.8 2179.55  1496.3 2209.84  1580.8 2224.64
#Mann= 3 , 0 , 0
       0      .1       0   548.8    .045       0   563.8      .1       0
Bank Sta=548.8,563.8
XS Rating Curve= 0 ,0
Exp/Cntr=0.3,0.1

Type RM Length L Ch R = 1 ,989.4   ,302.6,248.3,235.9
XS GIS Cut Line= 4
     1854867.152      178588.292     1854401.448      178839.772
     1854317.622      179240.277     1854243.109      179892.261
#Sta/Elev= 30
       0 1961.22   204.7 1937.46   314.6 1934.86   369.5 1930.39   394.4 1926.86
   429.4 1915.98   504.3 1907.02   534.3 1894.25   569.2 1866.38   589.2 1855.02
   604.1 1850.82   629.1    1835     654 1815.77     669 1810.86   723.9  1817.6
   738.8 1812.75   753.1 1812.55   768.1 1811.28   818.7 1817.47   938.4  1876.3
    1018 1896.21  1117.4 1931.81  1152.2 1947.31  1281.5 1997.12  1351.1 2032.48
  1430.6 2068.44  1455.5 2071.02  1470.4 2075.03  1500.2  2090.7  1594.7 2128.68
#Mann= 3 , 0 , 0
       0      .1       0   753.1    .045       0   768.1      .1       0
#XS Ineff= 2 , 0
          724.31 1817.54
Permanent Ineff=
       F       F
Bank Sta=753.1,768.1
XS Rating Curve= 0 ,0
Exp/Cntr=0.3,0.1

Type RM Length L Ch R = 1 ,741.1   ,249.9,352.5,393.7
XS GIS Cut Line= 4
     1854746.069       178606.92     1854177.911      178867.714
     1854103.398       179109.88     1854075.456      179650.096
#Sta/Elev= 30
       0 1924.34   109.2 1910.71   248.1 1907.13   332.4 1910.97     392 1907.44
   476.3 1886.42     511 1881.44   540.8 1874.39   580.5 1854.33   610.3 1846.87
   635.1 1827.76   659.9 1814.53   689.7 1808.03   758.8 1807.87   773.8 1807.49
     804 1805.34   818.9 1807.49   863.6 1834.88     953 1871.97   982.7 1891.22
  1017.5  1898.5  1047.3 1913.94  1106.8 1940.33  1166.4 1964.51  1230.9  1996.3
  1295.4 2032.56  1315.2 2041.21  1340.1 2047.74  1384.7 2073.22  1419.5  2084.9
#Mann= 3 , 0 , 0
       0      .1       0   758.8    .045       0   773.8      .1       0
Bank Sta=758.8,773.8
XS Rating Curve= 0 ,0
Exp/Cntr=0.3,0.1

Type RM Length L Ch R = 1 ,388.6   ,261.7,238.2,260.1
XS GIS Cut Line= 4
     1854736.755      178532.408     1854159.702      178726.283
     1853798.137      178785.371     1853507.298      179072.623
#Sta/Elev= 30
       0 1886.62    89.8 1864.83   149.7 1860.91   204.6 1854.19   284.4 1849.39
   324.3 1849.61     474 1856.83   528.9 1850.01   603.8  1851.5   613.7 1849.71
   643.4 1836.46   653.3 1828.92   673.1 1808.52     688 1808.72   707.8 1803.42
   722.6 1796.89   732.5 1795.56   762.2 1798.79   812.1 1797.03   827.1 1797.32
   856.3 1802.12   876.1 1816.36   940.5 1855.19   985.1 1887.69  1049.9  1927.2
  1084.8 1945.98  1164.6  1983.4  1204.4  1998.1  1299.2 2053.61  1383.9 2094.85
#Mann= 3 , 0 , 0
       0      .1       0   812.1    .045       0   827.1      .1       0
Bank Sta=812.1,827.1
XS Rating Curve= 0 ,0
Exp/Cntr=0.3,0.1

Type RM Length L Ch R = 1 ,150.4   ,123.9,150.4,168.8
XS GIS Cut Line= 4
     1854441.951      178595.298      1854160.73      178701.975
       1853941.7      178499.794     1853684.639      178512.452
#Sta/Elev= 30
       0 1827.95    14.8 1829.29    44.4 1837.05    88.8 1834.94   123.3 1846.01
   172.6 1846.01   202.2 1839.86     217 1839.29   236.7 1840.96   261.3 1847.38
   300.8    1843   335.6 1822.86   395.2 1807.08   410.1 1807.63     425 1802.49
   459.8  1798.9   474.6 1792.42   509.4 1797.66   533.3 1791.08   534.3 1790.94
   548.3 1791.98     574 1794.98   598.8 1792.64   618.6 1803.62   638.4 1818.05
   658.2 1827.44   707.7  1865.7   747.3 1887.72     777 1900.33   856.2 1916.86
#Mann= 3 , 0 , 0
       0      .1       0   533.3    .045       0   548.3      .1       0
#XS Ineff= 2 , 0
          508.41 1797.77
Permanent Ineff=
       F       F
Bank Sta=533.3,548.3
XS Rating Curve= 0 ,0
Exp/Cntr=0.3,0.1

Chan Stop Cuts=-1
Use User Specified Reach Order=0